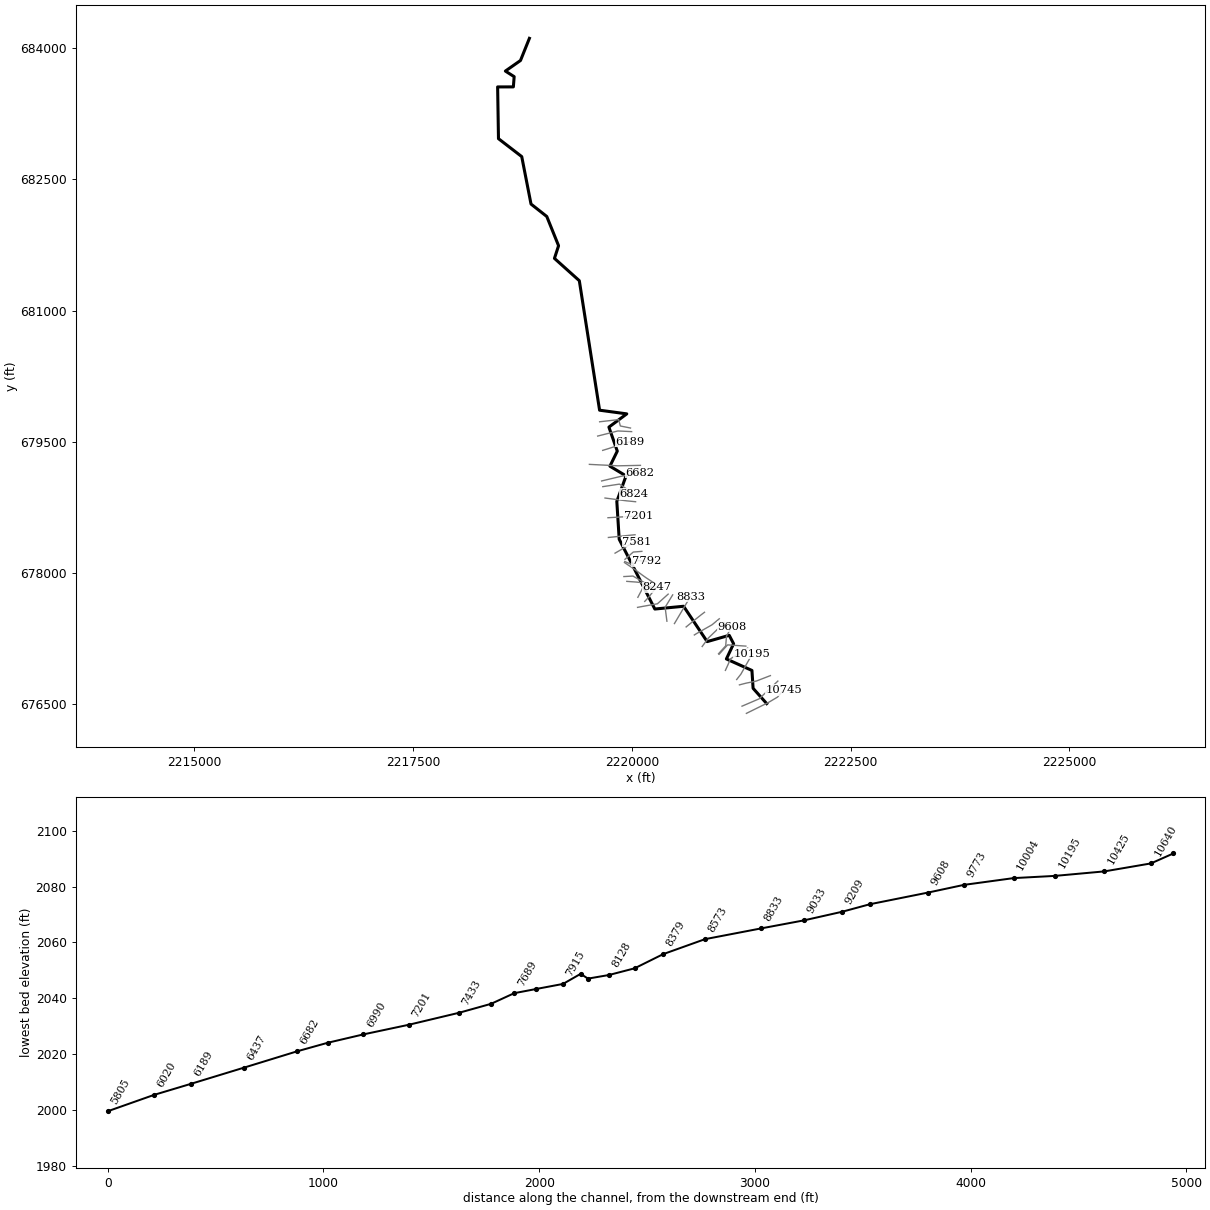
--- LAURELRN2.prj (project) ---

Proj Title=LAURELRN2
Current Plan=p01
Default Exp/Contr=0,0
English Units
Geom File=g01
Flow File=f01
Plan File=p01
BEGIN DESCRIPTION:
---------- MODELED AS PART OF WVEMD CTP PROGRAM, 2023----------
Stream Name: Laurel Run (II)
Flood Zone:  AFH
Upshur County, WV
HEC-RAS Version: RAS 6.3
Vertical Datum: NAVD88
Projection: NAD 1983 StatePlane West Virginia S FIPS 4702 (US Feet)
Terrain: 1-meter LIDAR (FEMA Region III 3DEP collected 2016-2018)
Land Use: 2019 NLCD
Hydrologic Method:
WV SIR2010-5033 regression equations
Additional Model Notes:
None
END DESCRIPTION:
DSS File=dss
DSS Export Rating Curves= 0
DSS Export Rating Curve Sorted= 0
DSS Export Volume Flow Curves= 0
DXF OffsetX= 0
DXF OffsetY= 0
DXF ScaleX= 0
DXF ScaleY= 0

--- LAURELRN2.p01 (plan) ---

Plan Title=Floodplain
Program Version=6.31
Short Identifier=Floodplain
Geom File=g01
Flow File=f01
Subcritical Flow
K Sum by GR= 0
Std Step Tol= 0.01
Critical Tol= 0.01
Num of Std Step Trials= 20
Max Error Tol= 0.3
Flow Tol Ratio= 0.001
Split Flow NTrial= 30
Split Flow Tol= 0.02
Split Flow Ratio= 0.02
Log Output Level= 0
Friction Slope Method= 1
Unsteady Friction Slope Method= 2
Unsteady Bridges Friction Slope Method= 1
Parabolic Critical Depth
Global Vel Dist= 0 , 0 , 0
Global Log Level= 0
CheckData=True
Encroach Param=-1 ,0,0, 0
Computation Interval=0.1SEC
Output Interval=1SEC
Instantaneous Interval=Max Profile
Mapping Interval=1HOUR
Computation Time Step Use Courant=        0
Computation Time Step Use Time Series=    0
Computation Time Step Count To Double=0
Computation Time Step Max Doubling=0
Computation Time Step Max Halving=0
Computation Time Step Residence Courant=0
Run HTab= 0
Run UNet= 0
Run Sediment= 0
Run PostProcess= 0
Run WQNet= 0
Run RASMapper=-1
UNET Theta= 0
UNET Theta Warmup= 0
UNET ZTol= 0
UNET ZSATol= 0
UNET MxIter= 0
UNET Max Iter WO Improvement= 0
UNET MaxInSteps= 0
UNET DtIC= 0
UNET DtMin= 0
UNET MaxCRTS= 0
UNET WFStab= 0
UNET SFStab= 0
UNET WFX= 1
UNET SFX= 1
UNET Gravity=32.17405
UNET 1D Methodology=Finite Difference
UNET DSS MLevel= 1
UNET Pardiso=0
UNET DZMax Abort= 0
UNET Use Existing IB Tables= 0
UNET Froude Reduction=False
UNET Froude Limit= 0
UNET Froude Power= 0
UNET D1 Cores= 0
UNET WindReference=Eulerian
UNET WindDragFormulation=Hsu (1988)
UNET D2 Coriolis=0
UNET D2 Cores= 0
UNET D2 Theta= 1
UNET D2 Theta Warmup= 1
UNET D2 Z Tol= 0.01
UNET D2 Volume Tol= 0.01
UNET D2 Max Iterations= 20
UNET D2 Equation= 0
UNET D2 RampUpFraction=0.1
UNET D2 TimeSlices= 1
UNET D2 Turbulence Formulation=Non-Conservative (original)
UNET D2 Eddy Viscosity=0.3
UNET D2 Transverse Eddy Viscosity=0.1
UNET D2 Smagorinsky Mixing=0
UNET D2 BCVolumeCheck=0
UNET D2 Cores=0
UNET D2 SolverType=PARDISO (Direct)
UNET D2 Minimum Iterations= 3
UNET D2 Maximum Iterations= 30
UNET D2 Restart Number= 10
UNET D2 Relaxation Coeff=1.3
UNET D2 SOR Precondition Iterations= 10
UNET D2 ILUT Maximum Fill= 8
UNET D2 ILUT Tolerance=1E-08
UNET D2 Convergence Tolerance=0.00001
UNET D1D2 MaxIter= 0
UNET D1D2 ZTol=0.01
UNET D1D2 QTol=0.1
UNET D1D2 MinQTol=1
DSS File=dss
Write IC File= 0
Write IC File at Fixed DateTime=0
Write IC File at Sim End=0
Echo Input=False
Echo Parameters=False
Echo Output=False
Write Detailed= 0
HDF Write Warmup=0
HDF Write Time Slices=0
HDF Flush=0
HDF Compression= 1
HDF Chunk Size= 1
HDF Spatial Parts= 1
HDF Use Max Rows=0
HDF Fixed Rows= 1
Calibration Method= 0
Calibration Iterations= 20
Calibration Max Change=0.05
Calibration Tolerance=0.2
Calibration Maximum=1.5
Calibration Minimum=0.5
Calibration Optimization Method= 1
WQ AD Non Conservative
WQ ULTIMATE=-1
WQ Max Comp Step=1HOUR
WQ Output Interval=15MIN
WQ Output Selected Increments= 0
WQ Create Restart=0
WQ Fixed Restart=0
WQ System Summary=0
WQ Write To DSS=0
Sorting and Armoring Iterations= 10
XS Update Threshold= 0.02
Bed Roughness Predictor= 0
Hydraulics Update Threshold= 0.02
Energy Slope Method= 1
Volume Change Method= 1
Sediment Retention Method= 0
Sediment TS Multiplier= 1
Warm Up Method= 0
XS Weighting Method= 0
Number of US Weighted Cross Sections= 1
Number of DS Weighted Cross Sections= 1
Upstream XS Weight=0
Main XS Weight=1
Downstream XS Weight=0
Number of DS XS's Weighted with US Boundary= 1
Upstream Boundary Weight= 1
Weight of XSs Associated with US Boundary= 0
Number of US XS's Weighted with DS Boundary= 1
Downstream Boundary Weight= 0.5
Weight of XSs Associated with DS Boundary= 0.5
Percentile Method= 0
Sediment Output Level= 3
Mass or Volume Output= 0
Output Increment Type= 1
Profile and TS Output Increment= 1
Transport Output Increment 1
XS Output Flag= 0
XS Output Increment= 10
Read HDF5 Sediment Hotstart= 0
Sediment Hotstart Type= 0
Write Gradation File= 0
Read Gradation Hotstart= 0
Write HDF5 File= 1
Write Binary Output= 1
Write DSS Sediment File= 0
DSS Sediment Output Type= 1
SV Curve= 0
Specific Gage Flag= 0
Subcell Erosion Methods= 0
Subcell Deposition Methods= 0
Advection Scheme= 1
Matrix Solver= 0
Implicit Weighting Factor= 1
Maximum Outer Loop Convergence Iterations= 5
Convergence Maximum Absolute= 0.001
Convergence RMSE= 0.0001
Grain Fractions Max Abs Error= 0.001
Max Subgrid Regions= 1
Max Subgrid Length Scale= 3.402823E+38
Initial Layer Thickness= 3.402823E+38
Min Layer Thickness= 3.402823E+38
Max Layer Thickness= 3.402823E+38
Number of Layers= 5

--- LAURELRN2.f01 (steady flow) ---

Flow Title=Flows
Program Version=6.31
Number of Profiles= 1
Profile Names=01pct
River Rch & RM=LAURELRN2,Main            ,10745
     340
River Rch & RM=LAURELRN2,Main            ,8031
     410
River Rch & RM=LAURELRN2,Main            ,5531
     456
River Rch & RM=LAURELRN2,Main            ,3180
     520
River Rch & RM=LAURELRN2,Main            ,1340
     520
Boundary for River Rch & Prof#=LAURELRN2,Main            , 1
Up Type= 0
Dn Type= 3
Dn Slope=0.008
DSS Import GetInterval= 0
DSS Import GetPeak= 0
DSS Import FillOption= 0

--- LAURELRN2.g01 (geometry) ---

Geom Title=Geometry
Program Version=6.31

River Reach=LAURELRN2       ,Main
Reach XY= 30
2221541.06568684676507.6290014982221385.44952826676682.503651753
2221372.17166768  676886.62430652221080.16995509677017.973453254
2221162.64255917677191.8753364242221112.53504784677288.255392998
2220860.51061751677216.1420201662220591.00131401   677620.262603
2220262.25656468677588.6130600122219854.98802225678386.409036592
2219827.83092435678818.1161784232219933.31102835679110.375108346
2219748.82123984679221.206579596 2219833.1822916679393.534318924
2219737.37474042679667.9084420952219941.49539517679819.374674588
2219630.80704017679861.2407325952219399.12902585681341.509097502
2219114.93963359681596.5384430892219162.07077293681741.165450424
2219027.20162009682075.5194405022218847.06156042682217.542778507
2218741.00927909682759.9376910922218475.19156925682964.830982089
2218465.49047318683556.2743530122218645.37331551683556.732357338
 2218654.4444916683673.6875040082218553.97257967683737.530552179
2218726.81540984683858.3492081762218828.74696451684111.661365584

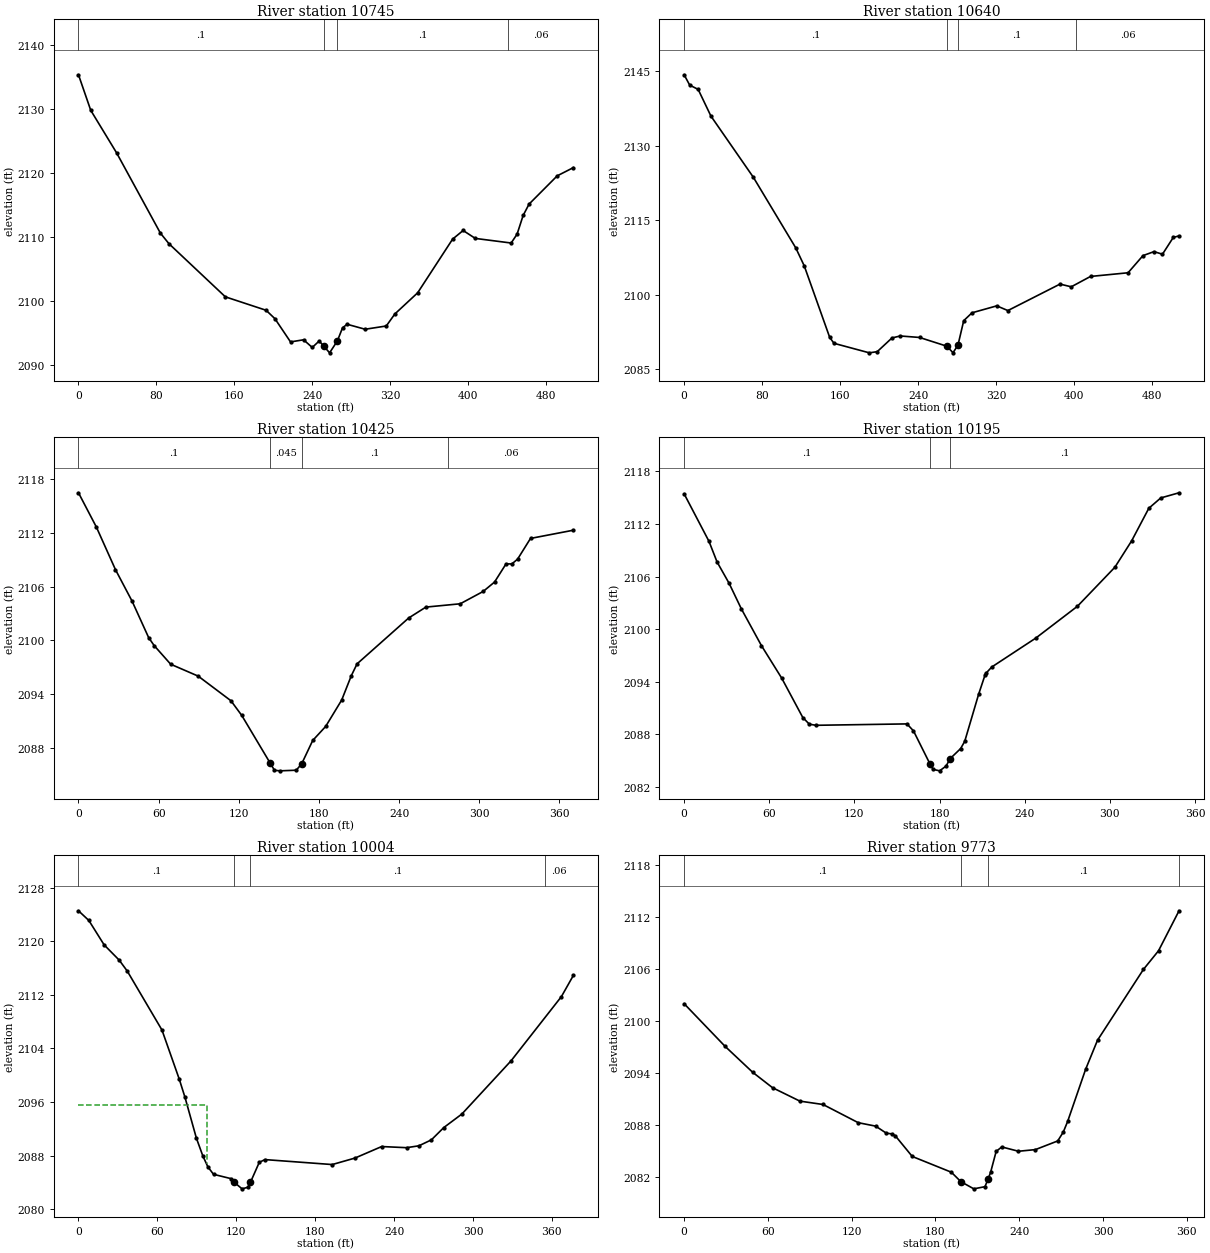
Type RM Length L Ch R = 1 ,10745   ,104.6,104.6,104.6
XS GIS Cut Line= 5
2221308.88878394676396.0007235492221513.66955911676496.965061169
2221552.45811819676515.7889207262221664.26043556676581.957639166
2221733.85167392676662.957277257
#Sta/Elev= 30
       0 2135.37    12.6 2129.81    39.2 2123.14    84.1  2110.6    92.9 2108.94
   150.8 2100.63   192.6 2098.53   201.7 2097.21   217.7 2093.58   231.1 2093.91
     240 2092.71   247.1 2093.72   251.9 2092.91   257.8 2091.87   265.82093.737
   271.1 2095.79   275.8 2096.34   294.3 2095.56     316 2096.07   324.8 2097.95
   348.2 2101.26   384.1 2109.66   394.9 2111.01   407.4 2109.77   444.2 2109.05
   450.3 2110.44   456.5 2113.36   462.6 2115.14   491.5 2119.56   508.1 2120.85
#Mann= 4 ,-1,0
       0      .1       0   251.9    .045       0   265.8      .1       0
  441.35     .06       0
Bank Sta=251.9,265.8
XS Rating Curve= 0 ,0
Exp/Cntr(USF)=0,0
Exp/Cntr=0.3,0.1

Type RM Length L Ch R = 1 ,10640   ,215.1,215.1,215.1
XS GIS Cut Line= 3
2221258.93977832676478.3526506852221454.10320615676561.985773558
2221668.48854384676765.179791408
#Sta/Elev= 30
       0 2144.33     5.7 2142.25    14.4 2141.38    27.5    2136      71 2123.67
   114.5 2109.44   123.2 2105.82   149.3 2091.41   153.7  2090.2     190 2088.28
   198.1 2088.52   213.2 2091.28   221.7 2091.68   241.5 2091.38   269.62089.612
   275.8  2088.3   280.9 2089.82   286.8 2094.76   295.3 2096.35   320.7 2097.75
   332.1  2096.8   385.6 2102.14   397.1 2101.59   416.9 2103.68   455.4 2104.42
   470.7 2107.88     482 2108.68   490.7 2108.16   501.8 2111.55   507.7 2111.85
#Mann= 4 ,-1,0
       0      .1       0   269.6    .045       0   280.9      .1       0
  402.33     .06       0
Bank Sta=269.6,280.9
XS Rating Curve= 0 ,0
Exp/Cntr(USF)=0,0
Exp/Cntr=0.3,0.1

Type RM Length L Ch R = 1 ,10425   ,230.2,230.2,230.2
XS GIS Cut Line= 4
2221229.33026679676721.8329466742221304.79683101676741.341310213
2221420.82025627676764.9566976562221583.19571215 676827.65088895
#Sta/Elev= 30
       0 2116.49    13.4 2112.66    27.7  2107.9    40.1 2104.39    52.5 2100.32
    56.6 2099.43      69 2097.34    89.6 2096.01   114.1 2093.26   122.2 2091.62
   143.22086.361   146.7 2085.49   150.8 2085.43     163  2085.5   167.1 2086.23
   175.3 2088.82     185 2090.39     197 2093.34   204.2 2096.06   208.5 2097.38
   247.1  2102.5     260 2103.72   285.7 2104.09   302.9 2105.47   311.4 2106.52
     320 2108.55   324.3 2108.54   328.6 2109.07   338.3 2111.39   370.4 2112.31
#Mann= 4 ,-1,0
       0      .1       0   143.2    .045       0   167.1      .1       0
  276.35     .06       0
Bank Sta=143.2,167.1
XS Rating Curve= 0 ,0
Exp/Cntr(USF)=0,0
Exp/Cntr=0.3,0.1

Type RM Length L Ch R = 1 ,10195   ,190.9,190.9,190.9
XS GIS Cut Line= 3
2221197.83380187676782.9422018572221246.34688714676844.757262126
2221378.58416797677080.280466444
#Sta/Elev= 30
       0 2115.44    17.5 2110.02    23.2 2107.66    31.7 2105.22    40.3 2102.31
    54.5  2098.1    68.8 2094.38    83.6  2089.9    88.2 2089.14    92.8 2089.01
     157 2089.17   161.6 2088.37   173.12084.634   175.4 2083.98     180 2083.81
   184.6 2084.36   187.4  2085.2   194.8 2086.35   197.7 2087.18   207.5 2092.56
   212.1  2094.8     213 2095.01   216.7 2095.66   247.7 2098.96   277.1  2102.6
   303.5 2107.06   315.3 2110.07   327.4 2113.79   335.8 2114.97   348.7 2115.56
#Mann= 3 ,-1,0
       0      .1       0   173.1    .045       0   187.4      .1       0
Bank Sta=173.1,187.4
XS Rating Curve= 0 ,0
Exp/Cntr(USF)=0,0
Exp/Cntr=0.3,0.1

Type RM Length L Ch R = 1 ,10004   ,230.7,230.7,230.7
XS GIS Cut Line= 4
2221068.89771424676887.4174378552221098.68631353676952.698836314
2221127.20731286677019.8816347282221323.93944889677142.232884792
#Sta/Elev= 30
       0 2124.57     7.9 2123.12    19.5 2119.48      31 2117.19    37.1 2115.56
    63.5 2106.75    76.6 2099.44      81  2096.7    89.7 2090.58    94.6 2087.93
    98.4 2086.31   102.7 2085.19   115.7 2084.56   118.42084.012   124.4 2083.02
   128.8 2083.25   130.82083.999   137.5 2086.98   141.8 2087.39     193 2086.65
   210.3 2087.62   230.6 2089.34   249.5 2089.17   258.9 2089.45   268.4 2090.34
   277.8 2092.17   291.6  2094.2     329 2102.15   367.3 2111.75   376.4 2114.92
#Mann= 4 ,-1,0
       0      .1       0   118.4    .045       0   130.8      .1       0
  354.74     .06       0
#XS Ineff= 2 , 0
           97.58 2095.58
Permanent Ineff=
       F       F
Bank Sta=118.4,130.8
XS Rating Curve= 0 ,0
Exp/Cntr(USF)=0,0
Exp/Cntr=0.3,0.1

Type RM Length L Ch R = 1 ,9773    ,165.3,165.3,165.3
XS GIS Cut Line= 3
2220996.63356782677071.3273799082221093.73540925677178.860318215
2221302.88940431677164.775874103
#Sta/Elev= 30
       0 2101.97    29.3 2097.05    49.1 2094.05    63.3 2092.27    82.9 2090.72
    99.5 2090.33   124.7 2088.23   137.2 2087.83   144.9 2087.01   148.8 2086.94
   151.3 2086.71   163.4 2084.33   191.4 2082.51   198.22081.423   207.5 2080.59
   215.5 2080.84   217.62081.683   219.5 2082.48   223.5 2084.91   227.5 2085.43
   239.5 2084.93   251.6 2085.12   267.6 2086.12   271.6 2087.15   274.7 2088.37
   287.6  2094.4   296.1 2097.75     329 2105.93   339.8 2108.08   354.5  2112.7
#Mann= 4 ,-1,0
       0      .1       0   198.2    .045       0   217.6      .1       0
  354.51     .06       0
Bank Sta=198.2,217.6
XS Rating Curve= 0 ,0
Exp/Cntr(USF)=0,0
Exp/Cntr=0.3,0.1

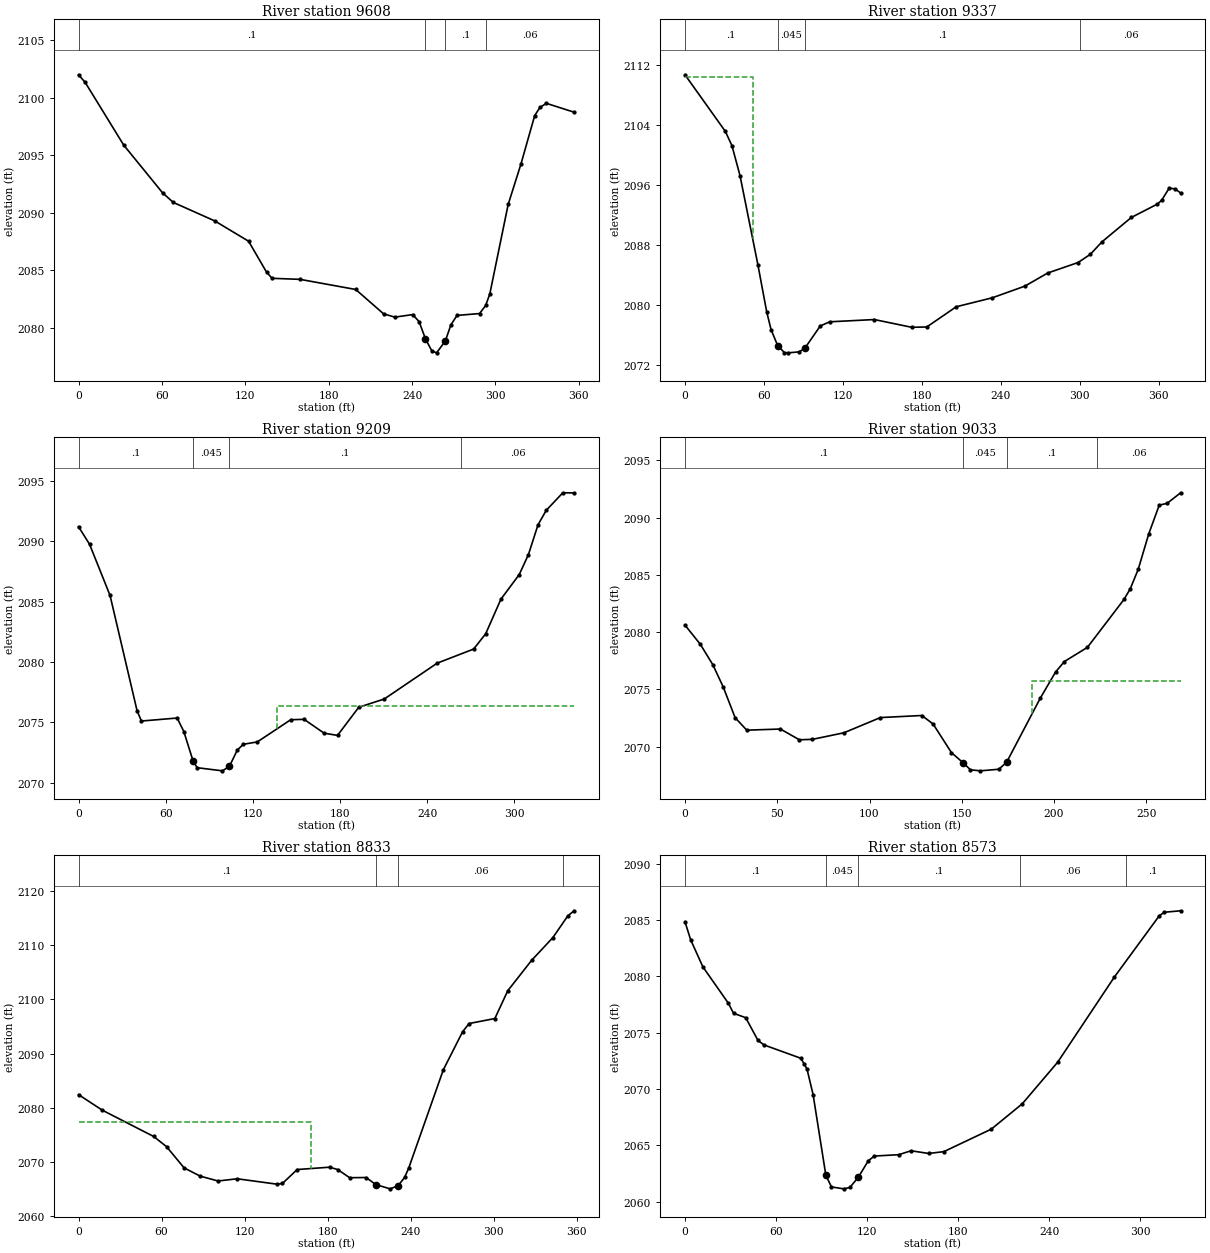
Type RM Length L Ch R = 1 ,9608    ,270.9,270.9,270.9
XS GIS Cut Line= 4
2220990.37381488677077.587132846 2221072.5330722677168.353550457
2221081.14023249677278.6816960012221141.39035452677386.662434193
#Sta/Elev= 30
       0 2101.99     4.8 2101.33    32.5 2095.89    60.5 2091.74    68.2 2090.91
    98.1  2089.3   122.4 2087.54   135.3 2084.86   139.3 2084.32   159.4 2084.23
   199.5 2083.35   219.5 2081.24   227.6 2080.95   240.5 2081.17   245.1 2080.56
   249.7 2079.06   254.3 2078.01   257.7 2077.85     2642078.885     268 2080.28
   272.4  2081.1   288.6 2081.26     293 2081.96     296 2082.97   309.2 2090.73
   318.4 2094.24   328.3 2098.45   332.1 2099.16   336.7 2099.51   356.7 2098.74
#Mann= 4 ,-1,0
       0      .1       0   249.7    .045       0     264      .1       0
  293.09     .06       0
Bank Sta=249.7,264
XS Rating Curve= 0 ,0
Exp/Cntr(USF)=0,0
Exp/Cntr=0.3,0.1

Type RM Length L Ch R = 1 ,9337    ,127.6,127.6,127.6
XS GIS Cut Line= 3
2220803.49497676677160.3784513312220874.56838551677257.555029833
2221059.16849967677435.167694777
#Sta/Elev= 30
       0 2110.65    30.7 2103.11    35.7 2101.21    41.8 2097.24    55.4 2085.37
    62.1  2079.1    65.4 2076.75    70.4 2074.62    75.5 2073.69    78.3 2073.65
    86.9 2073.78    91.32074.316   102.8 2077.23     110 2077.78   143.9 2078.08
   172.2 2077.05   183.7 2077.09   206.1 2079.78   233.6 2080.98   258.3 2082.53
   275.6 2084.27   298.7 2085.67     308 2086.76   316.9 2088.43   339.1 2091.66
   358.9 2093.44   362.2 2093.95   367.9 2095.57   372.4 2095.46   376.6 2094.92
#Mann= 4 ,-1,0
       0      .1       0    70.4    .045       0    91.3      .1       0
  300.39     .06       0
#XS Ineff= 2 , 0
        51.46708 2110.41
Permanent Ineff=
       T       F
Bank Sta=70.4,91.3
XS Rating Curve= 0 ,0
Exp/Cntr(USF)=0,0
Exp/Cntr=0.3,0.1

Type RM Length L Ch R = 1 ,9209    ,176.6,176.6,176.6
XS GIS Cut Line= 4
 2220713.7491343677292.1366206312220737.32625833677306.877796762
2220915.86771411677408.412554366 2220999.0420947677477.285486074
#Sta/Elev= 30
       0 2091.22     7.6 2089.76    21.7 2085.52    40.3 2075.96    43.3  2075.1
    67.9 2075.35    72.5 2074.23    78.92071.772    81.7 2071.23    99.1 2070.97
   103.9 2071.35   109.3 2072.69   113.4 2073.17   123.1 2073.37   146.1 2075.21
   155.3 2075.24   169.1 2074.09   178.3 2073.91   192.9 2076.24   210.5 2076.93
   246.9  2079.9     272 2081.07   280.3 2082.34   290.8 2085.21   303.4 2087.25
   309.7  2088.9   316.3 2091.37     322 2092.58   333.4 2094.03   341.2 2094.02
#Mann= 4 ,-1,0
       0      .1       0    78.9    .045       0   103.9      .1       0
   263.2     .06       0
#XS Ineff= 2 , 0
                          136.85         2076.38
Permanent Ineff=
       F       F
Bank Sta=78.9,103.9
XS Rating Curve= 0 ,0
Exp/Cntr(USF)=0,0
Exp/Cntr=0.3,0.1

Type RM Length L Ch R = 1 ,9033    ,200,200,200
XS GIS Cut Line= 4
2220620.20251468677383.9393366332220702.04341563677451.071641483
2220793.94441346677524.5924397482220830.05143156677551.614334507
#Sta/Elev= 30
       0 2080.61     8.3 2078.94    15.1 2077.15    20.7 2075.22    27.2 2072.52
    33.5 2071.44    51.7 2071.54      62  2070.6    69.1 2070.64    86.1 2071.21
   105.9 2072.54   128.4 2072.72   134.5 2071.97   144.4 2069.48   150.92068.569
   154.7 2067.98   160.1 2067.89   170.1 2068.03   174.3 2068.64   192.5 2074.22
   200.8 2076.51   205.6 2077.43   218.1 2078.67   237.9 2082.85   241.3 2083.78
   245.6 2085.47   251.3 2088.56     257 2091.08   261.3 2091.24   268.6 2092.16
#Mann= 4 ,-1,0
       0      .1       0   150.9    .045       0   174.3      .1       0
  223.54     .06       0
#XS Ineff= 2 , 0
                          188.11         2075.74
Permanent Ineff=
       F       F
Bank Sta=150.9,174.3
XS Rating Curve= 0 ,0
Exp/Cntr(USF)=0,0
Exp/Cntr=0.3,0.1

Type RM Length L Ch R = 1 ,8833    ,259.7,259.7,259.7
XS GIS Cut Line= 2
2220486.33059054 677422.505432832220669.09509011677730.424418704
#Sta/Elev= 30
       0 2082.41    17.1 2079.54    54.3 2074.67    63.6 2072.79    76.3 2068.86
    87.9 2067.34   100.8 2066.44   114.7 2066.85   143.4 2065.85   147.3 2065.98
     158 2068.56   181.4 2068.99   187.2 2068.56   195.9 2067.05   207.8 2067.08
   214.82065.779   225.1 2064.99     231 2065.57     231 2065.59   235.7 2067.14
   238.7 2068.93   263.6 2087.01   277.5 2094.03   282.2 2095.55   300.8 2096.47
   310.1  2101.6   327.3 2107.21   342.7 2111.43   353.6 2115.48   358.1 2116.39
#Mann= 4 ,-1,0
       0      .1       0   214.8    .045       0     231     .06       0
     350      .1       0
#XS Ineff= 2 , 0
          167.66 2077.26
Permanent Ineff=
       F       F
Bank Sta=214.8,231
XS Rating Curve= 0 ,0
Exp/Cntr(USF)=0,0
Exp/Cntr=0.3,0.1

Type RM Length L Ch R = 1 ,8573    ,193.6,193.6,193.6
XS GIS Cut Line= 3
2220400.33571994677449.4779340022220379.91327597677608.632152468
2220466.35108388677750.405429838
#Sta/Elev= 30
       0 2084.85     3.7 2083.26    11.8 2080.84    28.5 2077.63      32 2076.72
      40 2076.33    48.1 2074.31    52.1 2073.91    76.3 2072.73    78.5 2072.23
    80.4 2071.76    84.4  2069.5    92.8 2062.34    96.5 2061.31   104.6 2061.14
   108.6 2061.26   114.2 2062.17   120.7 2063.62   124.7 2064.05   140.8 2064.17
   148.9 2064.52   160.5 2064.28   170.5 2064.44   201.8 2066.44   222.2 2068.69
   245.5 2072.38   282.9 2079.95   312.4 2085.37   315.7 2085.69   326.5 2085.82
#Mann= 5 ,-1,0
       0      .1       0    92.8    .045       0   114.2      .1       0
  220.46     .06       0  290.46      .1       0
Bank Sta=92.8,114.2
XS Rating Curve= 0 ,0
Exp/Cntr(USF)=0,0
Exp/Cntr=0.3,0.1

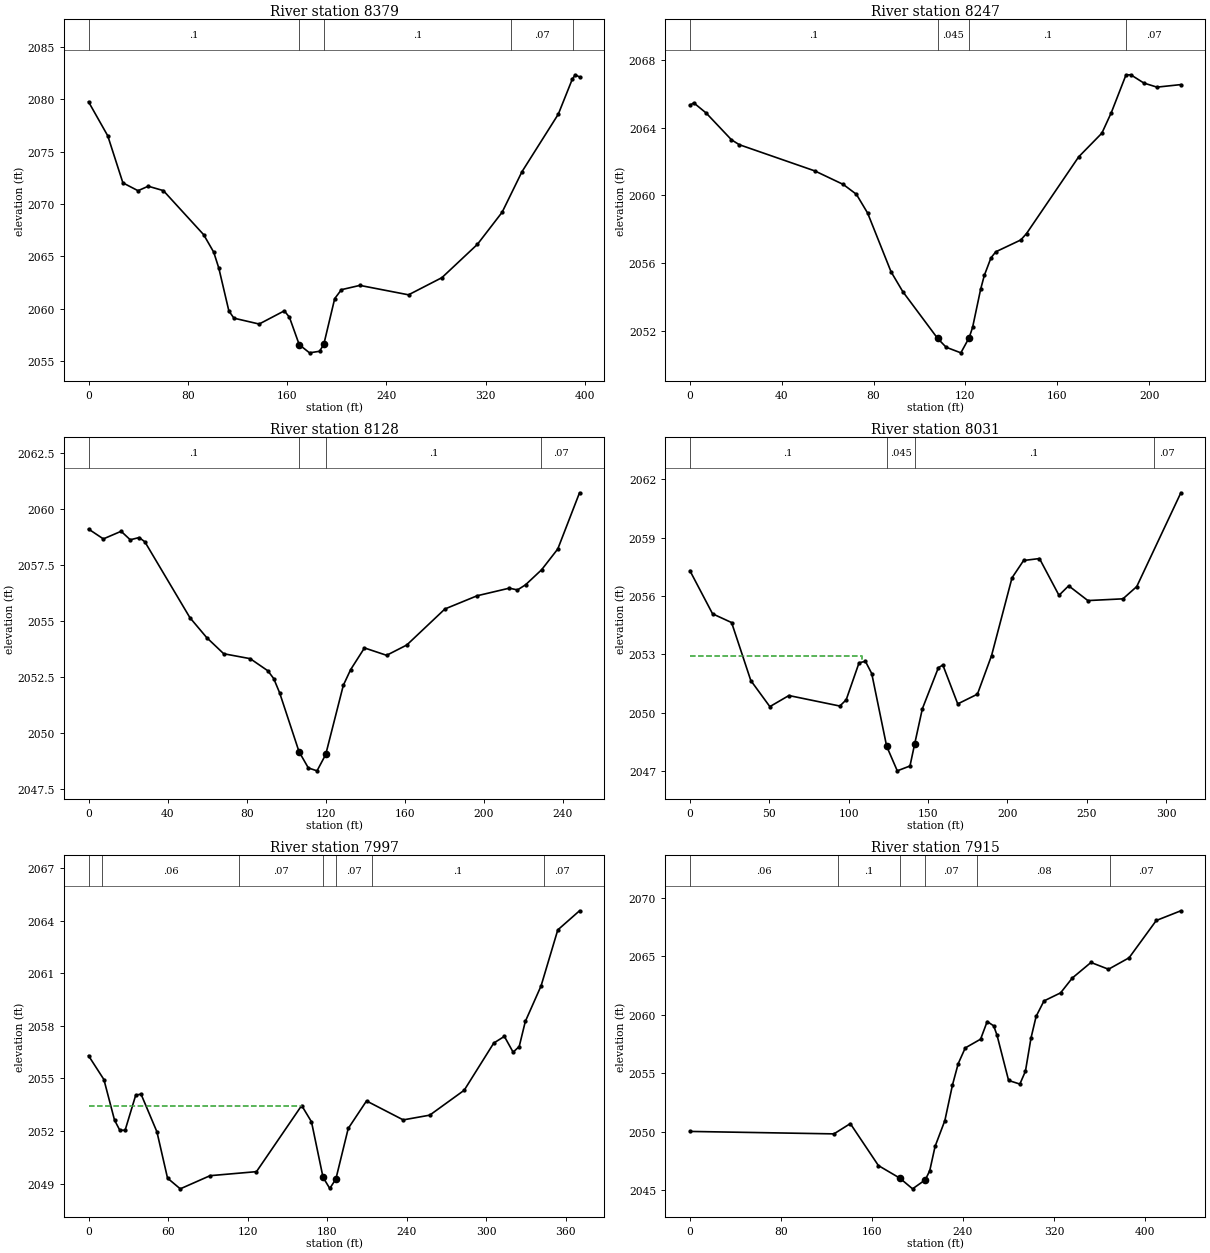
Type RM Length L Ch R = 1 ,8379    ,132.7,132.7,132.7
XS GIS Cut Line= 4
2220064.91729164677607.6671072242220124.90659063677618.969438919
2220291.83333566677648.5293833512220414.69725865677758.887061382
#Sta/Elev= 30
       0 2079.75    15.5  2076.5    27.7 2072.01    39.9 2071.26    48.1 2071.69
    60.3 2071.27    92.8 2067.06   100.9 2065.39     105 2063.87   113.1 2059.78
   117.2 2059.09   137.5 2058.53   157.8 2059.79   161.9 2059.18   169.82056.562
   178.1 2055.78   186.2 2055.93   189.62056.589   198.4 2060.96   203.8 2061.81
   218.7 2062.22   257.9 2061.32   284.8 2062.96   313.4 2066.14   333.3  2069.2
   349.3 2073.07   378.6 2078.57   389.9 2081.92   392.3 2082.33   395.7 2082.12
#Mann= 5 ,-1,0
       0      .1       0   169.8    .045       0   189.6      .1       0
  340.57     .07       0  390.57      .1       0
Bank Sta=169.8,189.6
XS Rating Curve= 0 ,0
Exp/Cntr(USF)=0,0
Exp/Cntr=0.3,0.1

Type RM Length L Ch R = 1 ,8247    ,118.9,118.9,118.9
XS GIS Cut Line= 4
2220146.99982193677675.9903234862220192.56405353 677724.70866017
2220249.94944502677798.3116622932220284.46384714677839.479443141
#Sta/Elev= 30
       0 2065.32     1.7 2065.46     7.1 2064.86    18.1 2063.28    21.5 2062.99
    54.4 2061.44    66.8 2060.64    72.5 2060.06    77.4 2058.95    87.6 2055.48
    92.7 2054.31   107.9 2051.54   111.6 2051.02     118 2050.69   121.62051.583
   123.1 2052.19   126.6 2054.44   128.2 2055.26   131.1  2056.3   133.2 2056.66
   144.1 2057.36   146.6 2057.74   169.3 2062.27   179.4 2063.67   183.5 2064.88
   189.9 2067.11     192 2067.12   197.7 2066.63   203.4 2066.39   213.8 2066.54
#Mann= 4 ,-1,0
       0      .1       0   107.9    .045       0   121.6      .1       0
  190.04     .07       0
Bank Sta=107.9,121.6
XS Rating Curve= 0 ,0
Exp/Cntr(USF)=0,0
Exp/Cntr=0.3,0.1

Type RM Length L Ch R = 1 ,8128    ,97,97,97
XS GIS Cut Line= 4
2220068.24505604677722.5572983742220110.44734681677802.519843722
2220131.73652903677846.3649392632220239.02226094677825.573130753
#Sta/Elev= 30
       0  2059.1     7.5 2058.66    16.5    2059    21.1 2058.62    25.6 2058.72
    28.5 2058.53    51.3 2055.14    59.8 2054.25    68.4 2053.53    81.8 2053.31
    90.7 2052.77    93.7 2052.42    96.7 2051.78   106.52049.155   111.2 2048.43
   115.6  2048.3     1202049.031   128.9 2052.12   132.6 2052.82   139.6 2053.79
   150.8 2053.46     161 2053.92   180.3 2055.53   196.6 2056.12   212.9 2056.46
     217 2056.38   221.1 2056.61   229.2 2057.28   237.4 2058.21   248.4 2060.72
#Mann= 4 ,-1,0
       0      .1       0   106.5    .045       0     120      .1       0
  229.16     .07       0
Bank Sta=106.5,120
XS Rating Curve= 0 ,0
Exp/Cntr(USF)=0,0
Exp/Cntr=0.3,0.1

Type RM Length L Ch R = 1 ,8031    ,34.2,34.2,34.2
XS GIS Cut Line= 4
2219941.90334572677904.9011955222220047.82374194677897.031225708
2220093.74104966677892.3658308052220237.68107663677829.506596526
#Sta/Elev= 30
       0  2057.3    14.3 2055.08    26.3 2054.63    38.4 2051.65    50.4 2050.31
    62.4 2050.88    94.5 2050.34    98.5 2050.66   106.6 2052.56   110.6 2052.64
   114.6 2052.01     1242048.274   130.7 2047.01   138.7 2047.26   141.62048.372
   146.5  2050.2   156.6 2052.31   159.4 2052.45   168.8 2050.45   181.2 2050.95
   190.1 2052.93     203 2056.93   210.3 2057.82   220.3 2057.92   232.6 2056.03
   238.7 2056.52   250.8 2055.76   272.9 2055.85   281.6 2056.48   309.4  2061.3
#Mann= 4 ,-1,0
       0      .1       0     124    .045       0   141.6      .1       0
  292.37     .07       0
#XS Ineff= 2 , 0
          108.58 2052.89
Permanent Ineff=
       F       F
Bank Sta=124,141.6
XS Rating Curve= 0 ,0
Exp/Cntr(USF)=0,0
Exp/Cntr=0.3,0.1

Type RM Length L Ch R = 1 ,7997    ,81.7,81.7,81.7
XS GIS Cut Line= 3
2219908.63009213677959.8147039462220012.21271851677965.511647627
2220243.59645881677833.058181817
#Sta/Elev= 30
       0  2056.3    11.6 2054.94    19.6 2052.63    23.6 2052.05    27.6 2052.05
    35.6 2054.05    39.6 2054.11    51.6 2051.96    59.6 2049.32    69.2 2048.71
    91.7 2049.46   126.7 2049.69   160.8 2053.46   168.2 2052.53   176.9 2049.37
     182 2048.73   186.62049.272   195.9 2052.15   209.7 2053.72   237.4 2052.64
   257.4 2052.91   283.4 2054.33   305.7 2057.02   313.7  2057.4   320.3  2056.5
   324.9 2056.82   329.5 2058.25   341.4 2060.28     354 2063.47   370.4 2064.56
#Mann= 7 ,-1,0
       0      .1       0      10     .06       0  113.74     .07       0
   176.9    .045       0   186.6     .07       0  213.74      .1       0
  343.74     .07       0
#XS Ineff= 2 , 0
          161.06 2053.46
Permanent Ineff=
       F       F
Bank Sta=176.9,186.6
XS Rating Curve= 0 ,0
Exp/Cntr(USF)=0,0
Exp/Cntr=0.3,0.1

Type RM Length L Ch R = 1 ,7915    ,122.9,122.9,122.9
XS GIS Cut Line= 5
2219915.03893878678119.901820026 2220040.7958876678035.592782502
2220105.51041168677986.740231902 2220160.0172104677947.515055049
2220270.22798557677875.121012313
#Sta/Elev= 30
       0 2050.01   126.6  2049.8     141 2050.68   165.7 2047.09   184.6 2046.01
   195.7  2045.1   206.9 2045.87   210.8 2046.65   215.5 2048.73   224.1 2050.94
   230.8 2053.99   235.8  2055.8     242 2057.15   255.5  2057.9   261.3 2059.41
     267 2059.04   269.9 2058.25   280.1 2054.37     290 2054.06   294.9 2055.16
   299.8    2058   304.3 2059.85   311.2 2061.17   325.8 2061.86   336.1 2063.13
   352.5 2064.46   367.9 2063.88     386 2064.86   409.9 2068.05   431.5 2068.88
#Mann= 6 ,-1,0
       0     .06       0     130      .1       0   184.6    .045       0
   206.9     .07       0  252.49     .08       0  369.64     .07       0
Bank Sta=184.6,206.9
XS Rating Curve= 0 ,0
Exp/Cntr(USF)=0,0
Exp/Cntr=0.3,0.1

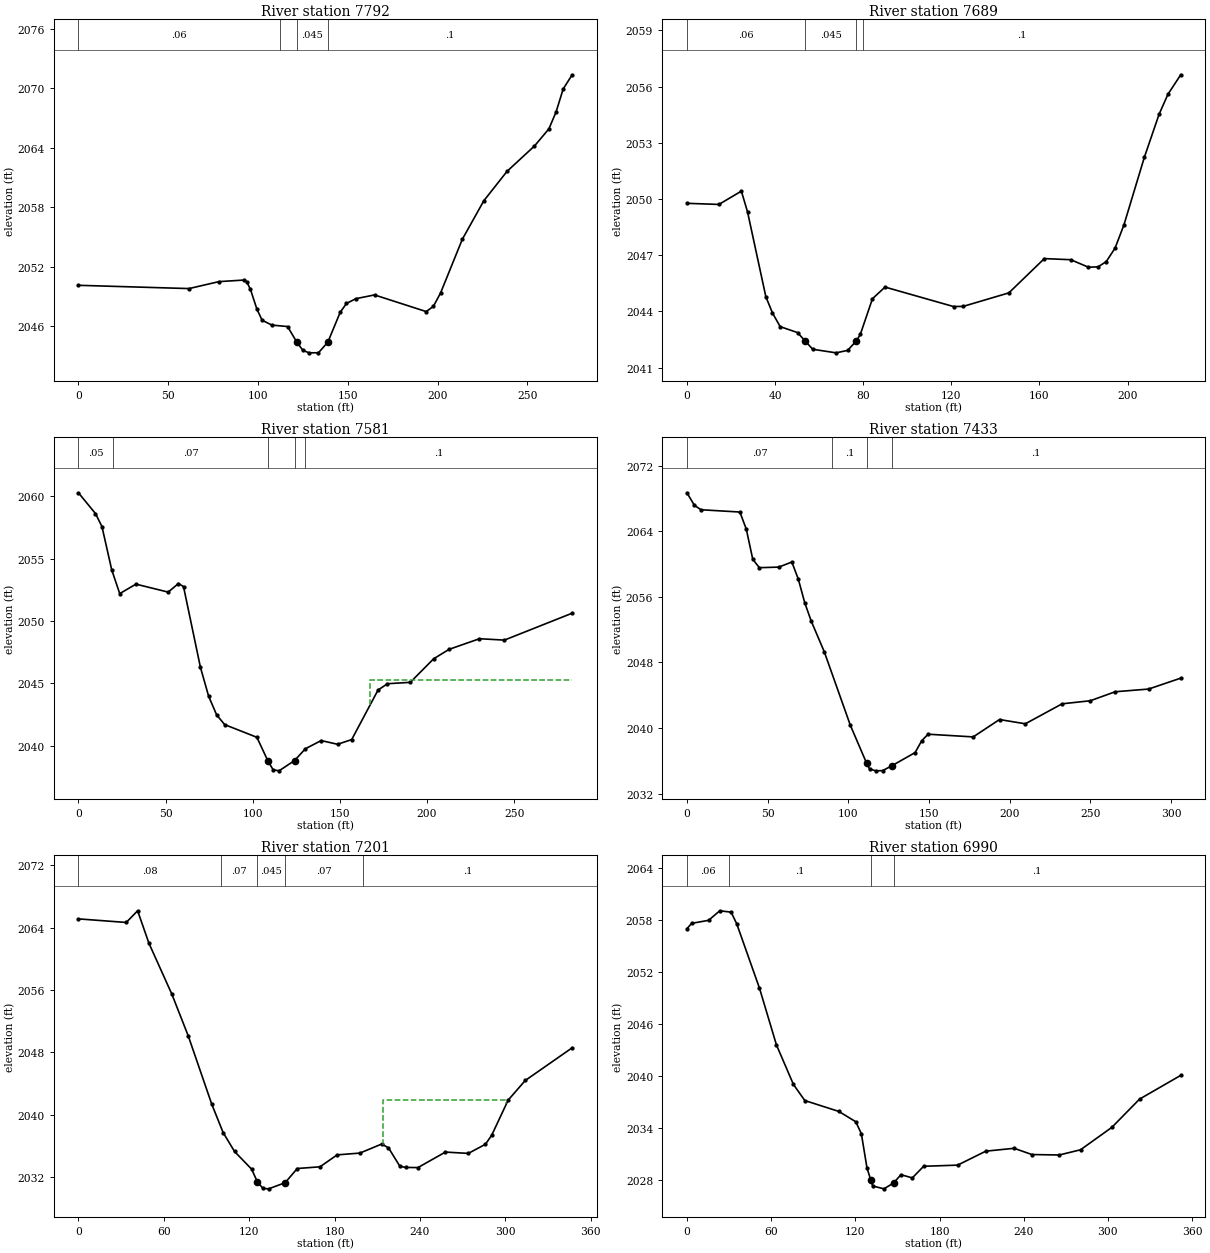
Type RM Length L Ch R = 1 ,7792    ,103.1,103.1,103.1
XS GIS Cut Line= 4
2219919.56579546678131.3510870422220004.27316346678094.901249902
2220062.28487609678143.1587807642220169.06749757678132.891221006
#Sta/Elev= 30
       0 2050.12    61.6 2049.79    78.2 2050.49    92.2 2050.65    93.8 2050.46
    95.8 2049.71    99.4 2047.72   102.3  2046.6   107.7 2046.11   116.5 2045.96
   121.52044.425     125 2043.56   128.5 2043.31   133.7 2043.32   138.9 2044.38
   145.8  2047.4   149.3 2048.29   154.5 2048.77   164.9 2049.15   193.7 2047.47
   197.7    2048   201.7 2049.35   213.8 2054.76   225.8 2058.65   238.7 2061.61
     254 2064.17     262 2065.89     266 2067.59     270 2069.93     275 2071.35
#Mann= 4 ,-1,0
       0     .06       0  112.22      .1       0   121.5    .045       0
   138.9      .1       0
Bank Sta=121.5,138.9
XS Rating Curve= 0 ,0
Exp/Cntr(USF)=0,0
Exp/Cntr=0.3,0.1

Type RM Length L Ch R = 1 ,7689    ,107.5,107.5,107.5
XS GIS Cut Line= 3
2219921.26944982678157.2709712312220015.52564839 678239.97616508
2220113.94020867678247.830848294
#Sta/Elev= 30
       0 2049.77    14.5 2049.71    24.7 2050.42    27.5 2049.31    35.8 2044.79
    38.8 2043.92    42.3 2043.19    50.2 2042.87    53.62042.428    57.1 2041.98
    67.7 2041.79    72.9 2041.92    76.92042.427    78.7 2042.78    84.2 2044.68
    89.9  2045.3     121 2044.26   125.4 2044.27   146.1 2044.99   162.2 2046.82
   174.2 2046.76   182.2 2046.36   186.6 2046.38   190.3 2046.66   194.3 2047.38
   198.3 2048.61   207.6 2052.23   214.3 2054.53   218.3 2055.59   224.1 2056.63
#Mann= 4 ,-1,0
       0     .06       0    53.6    .045       0    76.9     .06       0
      80      .1       0
Bank Sta=53.6,76.9
XS Rating Curve= 0 ,0
Exp/Cntr(USF)=0,0
Exp/Cntr=0.3,0.1

Type RM Length L Ch R = 1 ,7581    ,148.1,148.1,148.1
XS GIS Cut Line= 3
2219807.67333765 678227.20601087 2219979.4331336678327.346408507
 2220057.1399466 678360.41850924
#Sta/Elev= 30
       0 2060.28     9.8 2058.61    13.5 2057.57    19.1  2054.1    23.7 2052.19
      33 2052.95    51.5 2052.31    57.4    2053    60.3 2052.75      70 2046.28
    74.7 2043.96    79.3 2042.46    83.9 2041.68   102.4 2040.66   108.8 2038.74
   111.7 2038.06   115.1 2037.97     1242038.795   130.2 2039.74   139.3  2040.4
   148.7  2040.1   156.8 2040.48   171.9 2044.45   177.3 2044.96   190.4 2045.07
   203.8 2046.96   212.7 2047.72   230.1 2048.57   244.4 2048.46   283.3 2050.62
#Mann= 5 ,-1,0
       0     .05       0      20     .07       0   108.8    .045       0
     124     .07       0     130      .1       0
#XS Ineff= 2 , 0
                          167.32         2045.29
Permanent Ineff=
       F       F
Bank Sta=108.8,124
XS Rating Curve= 0 ,0
Exp/Cntr(USF)=0,0
Exp/Cntr=0.3,0.1

Type RM Length L Ch R = 1 ,7433    ,232.8,232.8,232.8
XS GIS Cut Line= 3
2219731.56614085678406.5192444162219918.57625989 678426.08097235
 2220036.0042065678437.841116173
#Sta/Elev= 30
       0  2068.7     4.6 2067.17     8.7 2066.63    32.8 2066.35    36.8 2064.25
    40.8 2060.57    44.9 2059.56    56.9 2059.63      65 2060.25      69 2058.17
      73 2055.28      77 2053.05    85.1  2049.3   101.3 2040.31   111.42035.672
   113.2 2034.98   117.2 2034.77   121.3  2034.8     127 2035.39   141.4    2037
   145.4 2038.41   149.4 2039.24   177.4 2038.91   193.7 2041.03   209.7 2040.51
   232.5 2042.95   249.9 2043.32   265.4 2044.42   286.1 2044.75     306 2046.08
#Mann= 4 ,-1,0
       0     .07       0      90      .1       0   111.4    .045       0
     127      .1       0
Bank Sta=111.4,127
XS Rating Curve= 0 ,0
Exp/Cntr(USF)=0,0
Exp/Cntr=0.3,0.1

Type RM Length L Ch R = 1 ,7201    ,210.3,210.3,210.3
XS GIS Cut Line= 2
 2219726.6518627678632.3229085952220073.12918786678652.041130352
#Sta/Elev= 30
       0 2065.14    33.6 2064.68    41.6 2066.18    49.6 2061.99    65.6  2055.5
    77.2 2050.11    93.7 2041.35   101.7  2037.7   109.7 2035.28   121.7 2033.01
   125.7  2031.4   129.7 2030.53   133.7 2030.48   145.32031.272   153.8 2033.09
   169.8 2033.31   181.8 2034.84   197.8 2035.07   213.1 2036.23   217.9 2035.75
   225.9 2033.38   229.9 2033.23   238.6 2033.21   257.9  2035.2     274 2035.03
     286  2036.2   290.4 2037.35     302 2041.87     314 2044.39     347 2048.59
#Mann= 5 ,-1,0
       0     .08       0     100     .07       0   125.7    .045       0
   145.3     .07       0     200      .1       0
#XS Ineff= 1 ,-1
213.9466300.6426 2041.87
Permanent Ineff=
       T
Bank Sta=125.7,145.3
XS Rating Curve= 0 ,0
Exp/Cntr(USF)=0,0
Exp/Cntr=0.3,0.1

Type RM Length L Ch R = 1 ,6990    ,165.9,165.9,165.9
XS GIS Cut Line= 3
2219692.92615572678857.4099713142219937.32700349678825.531599866
2220042.28039035678815.156789227
#Sta/Elev= 30
       0 2056.99     3.3 2057.61    15.4 2057.96    23.4 2059.06    31.5  2058.9
    35.5 2057.55    51.7 2050.14    63.8  2043.6    75.9 2039.05      84  2037.2
   108.2 2035.95   120.3 2034.76   124.3 2033.38   128.3 2029.44     131 2028.04
   132.4 2027.36   140.4 2027.03   147.3 2027.71   152.5 2028.66   160.6 2028.29
   168.7 2029.63   192.9 2029.76     213 2031.37   233.2  2031.7   245.8 2030.98
   265.4 2030.93   280.5 2031.53   302.8 2034.11   322.6 2037.37   351.9  2040.1
#Mann= 4 ,-1,0
       0     .06       0      30      .1       0     131    .045       0
   147.3      .1       0
Bank Sta=131,147.3
XS Rating Curve= 0 ,0
Exp/Cntr(USF)=0,0
Exp/Cntr=0.3,0.1

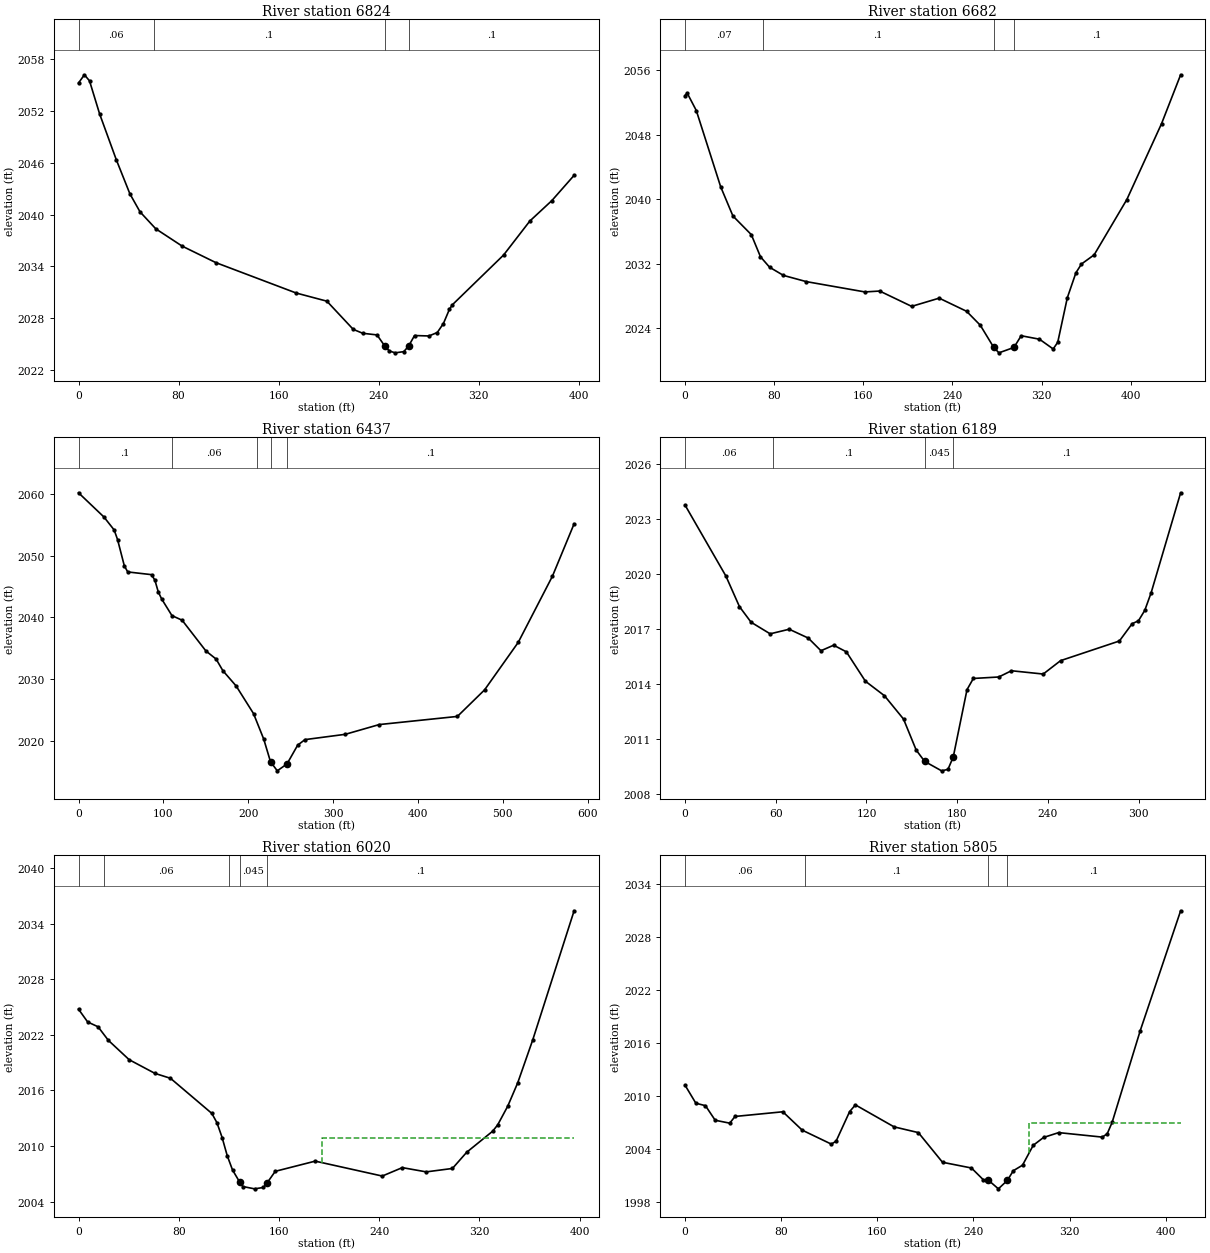
Type RM Length L Ch R = 1 ,6824    ,142.7,142.7,142.7
XS GIS Cut Line= 3
  2219667.503192678987.4182866432219857.86374991679016.526818556
2220026.97045912678902.864932038
#Sta/Elev= 30
       0  2055.2     4.7 2056.15     8.8 2055.45    16.9 2051.62    30.2 2046.34
    41.1 2042.39    49.2 2040.31    61.8 2038.35    82.9 2036.35   109.9 2034.44
   174.1 2030.93   198.6 2029.99   219.7 2026.73   227.3 2026.28   238.7 2026.09
     2452024.788   248.5 2024.24   253.2 2024.02   260.1 2024.16   263.92024.788
   268.7 2026.02   280.2 2025.97   286.9 2026.37   291.8 2027.41   296.6 2029.05
     299 2029.58   339.9 2035.32   360.9 2039.25   378.5 2041.61   396.3 2044.53
#Mann= 4 ,-1,0
       0     .06       0      60      .1       0     245    .045       0
   263.9      .1       0
Bank Sta=245,263.9
XS Rating Curve= 0 ,0
Exp/Cntr(USF)=0,0
Exp/Cntr=0.3,0.1

Type RM Length L Ch R = 1 ,6682    ,244.9,244.9,244.9
XS GIS Cut Line= 4
2219654.31304794679052.4800942432219873.64670756 679104.93395876
2220032.36046999679139.0223225422220088.50490249679148.666157728
#Sta/Elev= 30
       0 2052.84     1.9 2053.15    10.1 2050.98      32 2041.52      43  2037.9
    59.5 2035.59    67.7 2032.85    75.9 2031.55    88.3 2030.54   108.8 2029.77
   161.4 2028.49   174.7  2028.6   203.4  2026.7   228.1 2027.72   252.7 2026.09
     265 2024.36   276.9 2021.65   281.7 2020.94   295.2 2021.61   301.7 2023.06
   318.1 2022.63   330.4 2021.42   334.5 2022.25   343.1 2027.77   350.8 2030.86
   355.8 2031.95   367.2 2033.09   396.5 2039.94   427.7 2049.36   444.8 2055.41
#Mann= 4 ,-1,0
       0     .07       0      70      .1       0   276.9    .045       0
   295.2      .1       0
Bank Sta=276.9,295.2
XS Rating Curve= 0 ,0
Exp/Cntr(USF)=0,0
Exp/Cntr=0.3,0.1

Type RM Length L Ch R = 1 ,6437    ,247.5,247.5,247.5
XS GIS Cut Line= 3
2219514.26277883679242.1314905312219840.47784167679225.637644802
  2220097.735983679230.823989663
#Sta/Elev= 30
       0 2060.19      30 2056.26      42 2054.16      46 2052.61      54 2048.34
      58 2047.36      86 2046.92      90 2046.02      94 2044.11      98 2042.97
   110.1 2040.28   122.1 2039.53   150.1 2034.55   162.1 2033.24   170.1 2031.35
   185.7 2028.88   206.2  2024.4   218.2 2020.27   226.2  2016.6   234.2 2015.12
   245.7 2016.25   258.2 2019.28   266.8 2020.18   314.3 2021.04   354.3 2022.62
   446.4 2023.94   478.4 2028.24   518.1 2035.95   558.4 2046.68   583.9 2055.16
#Mann= 5 ,-1,0
       0      .1       0     110     .06       0     210      .1       0
   226.2    .045       0   245.7      .1       0
Bank Sta=226.2,245.7
XS Rating Curve= 0 ,0
Exp/Cntr(USF)=0,0
Exp/Cntr=0.3,0.1

Type RM Length L Ch R = 1 ,6189    ,168.9,168.9,168.9
XS GIS Cut Line= 3
2219666.35056535679402.0750185272219722.25742823679419.170505523
2219978.68973318679501.413659183
#Sta/Elev= 30
       0 2023.75      27 2019.89      36 2018.22    43.7 2017.37    56.3 2016.74
    68.9 2016.99    81.5 2016.51    89.9 2015.82    98.3 2016.12   106.7 2015.76
   119.3 2014.16   131.9 2013.37   144.5  2012.1   152.9 2010.41   158.52009.793
   169.7 2009.28   173.9 2009.36   177.42010.033   186.5  2013.7   190.7 2014.31
   207.5 2014.39   215.9 2014.73   236.9 2014.55   248.4 2015.28   287.3 2016.35
   295.7 2017.29   299.9 2017.45   304.1 2018.02   308.3 2018.98   327.8 2024.42
#Mann= 4 ,-1,0
       0     .06       0   58.46      .1       0   158.5    .045       0
   177.4      .1       0
Bank Sta=158.5,177.4
XS Rating Curve= 0 ,0
Exp/Cntr(USF)=0,0
Exp/Cntr=0.3,0.1

Type RM Length L Ch R = 1 ,6020    ,215.5,215.5,215.5
XS GIS Cut Line= 3
 2219609.0575819679565.637245469 2219839.5659573 679623.96910534
2219997.06776359679616.467102308
#Sta/Elev= 30
       0 2024.76     7.3 2023.38    15.6 2022.86    23.8  2021.4    40.4 2019.31
      61 2017.83    73.4  2017.3   106.4 2013.51   110.5  2012.5   114.6 2010.91
   118.7 2008.94   122.9 2007.41   128.6  2006.1   131.1 2005.62   140.5 2005.37
   147.6 2005.52   150.4 2005.99     157 2007.26   188.9 2008.36   242.4 2006.75
   258.4 2007.66   277.5  2007.2   298.4 2007.57   309.8 2009.32   330.5 2011.59
   334.5 2012.27   342.5 2014.28   350.5 2016.81   362.5 2021.45   395.5 2035.38
#Mann= 5 ,-1,0
       0      .1       0      20     .06       0     120      .1       0
   128.6    .045       0   150.4      .1       0
#XS Ineff= 2 , 0
                          194.48         2010.89
Permanent Ineff=
       F       F
Bank Sta=128.6,150.4
XS Rating Curve= 0 ,0
Exp/Cntr(USF)=0,0
Exp/Cntr=0.3,0.1

Type RM Length L Ch R = 1 ,5805    ,273.8,273.8,273.8
XS GIS Cut Line= 4
2219631.25870024679728.8666881182219848.72181708 679753.68838621
2219868.23018062679680.7887119292219984.03819231679657.566699647
#Sta/Elev= 30
       0 2011.23       9 2009.19      17 2008.91    25.1 2007.26    37.2 2006.93
    41.6 2007.69    81.4 2008.22    97.5 2006.14   121.7 2004.56   125.7 2004.88
     137 2008.24   141.8    2009     174 2006.51   194.2 2005.86   214.3  2002.5
   238.4 2001.85   248.4  2000.5   252.5 2000.47   260.8 1999.49   268.32000.447
   273.2 2001.54   280.9 2002.17   289.8 2004.42   298.4 2005.31     311 2005.86
   347.3 2005.35   351.4 2005.73   355.5 2007.03   378.9 2017.42   412.5 2030.99
#Mann= 4 ,-1,0
       0     .06       0     100      .1       0   252.5    .045       0
   268.3      .1       0
#XS Ineff= 2 , 0
                           286.2         2006.96
Permanent Ineff=
       F       F
Bank Sta=252.5,268.3
XS Rating Curve= 0 ,0
Exp/Cntr(USF)=0,0
Exp/Cntr=0.3,0.1