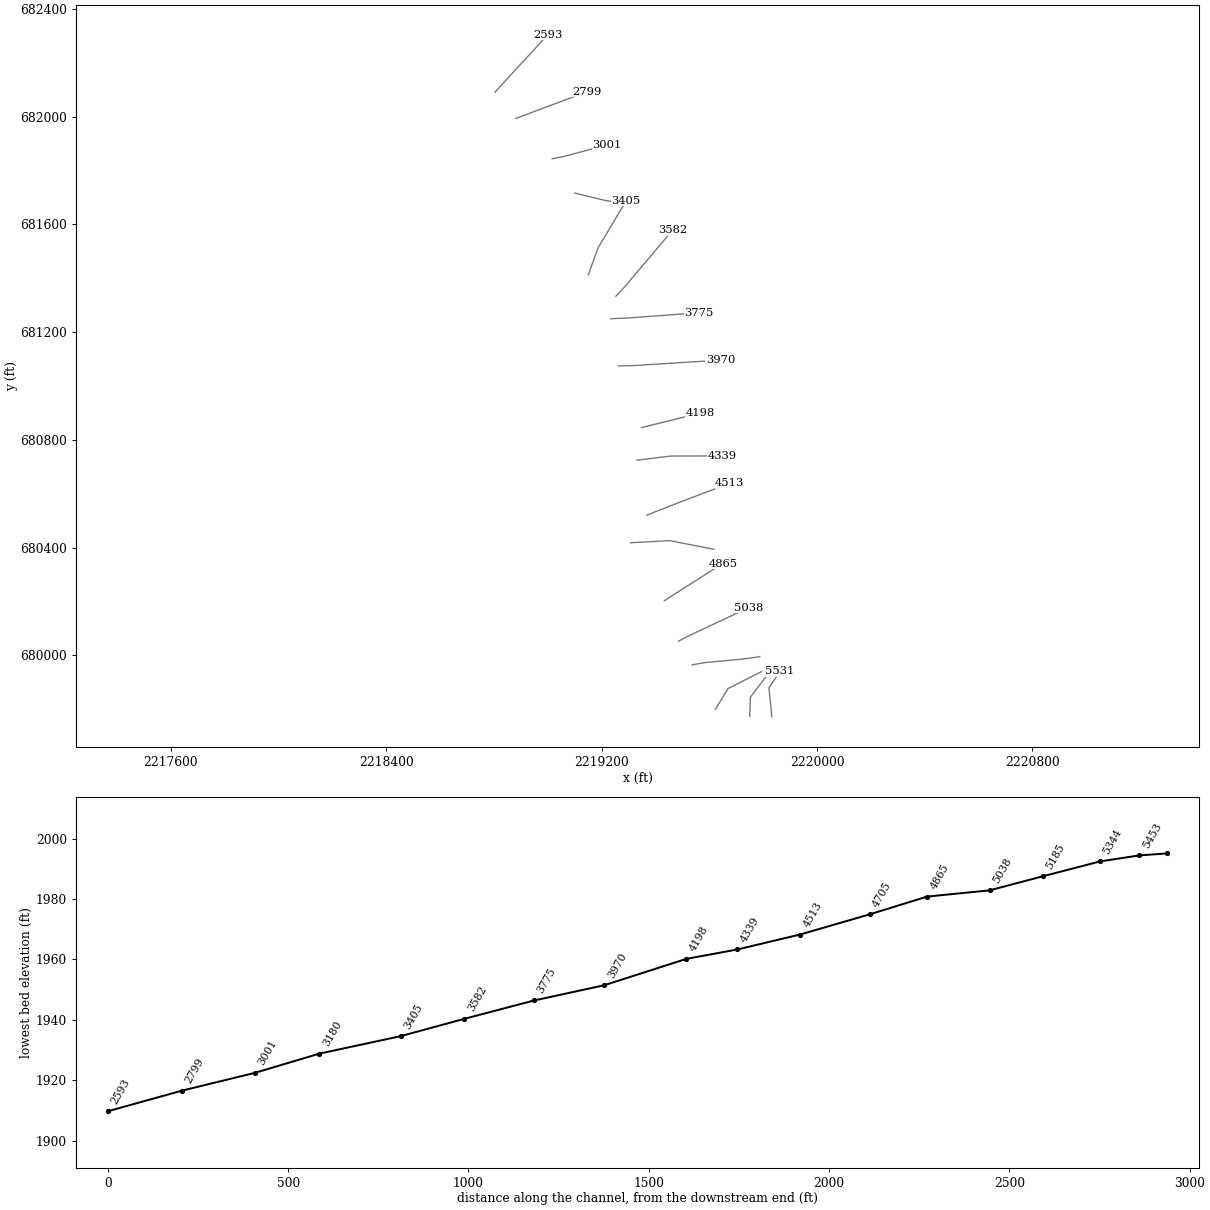
HEC-RAS study LAURELRN2.prj: LAURELRN2

--- LAURELRN2.g01 (geometry) --- (continued)

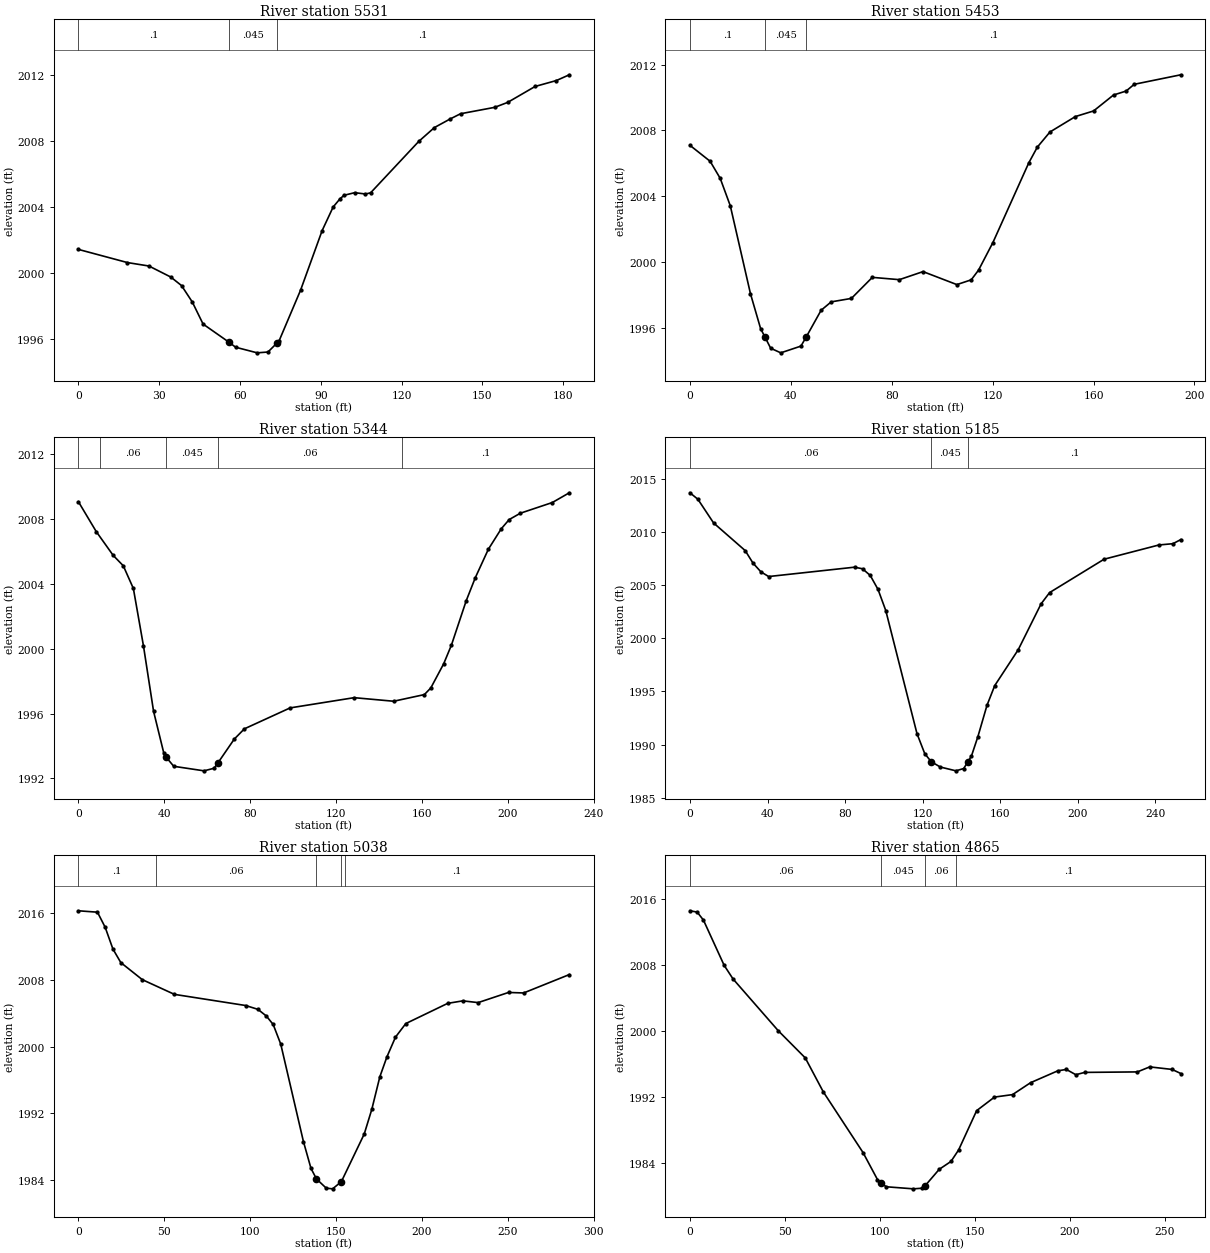
Type RM Length L Ch R = 1 ,5531    ,77.7,77.7,77.7
XS GIS Cut Line= 3
2219832.39248028679771.1026766342219821.43791264679879.083414828
2219862.90877586679940.116005981
#Sta/Elev= 30
       0 2001.42    18.2 2000.62    26.2 2000.41    34.3 1999.74    38.3 1999.22
    42.3 1998.22    46.3 1996.88    55.8 1995.79    58.4 1995.47    66.4 1995.13
    70.4 1995.18    73.7 1995.72    74.5 1995.85    82.5 1998.94    90.5 2002.56
    94.6    2004      97 2004.47    98.6 2004.71   102.6 2004.87   106.6 2004.79
   108.5 2004.86   126.4 2007.99   132.2 2008.83   137.9 2009.34   141.9 2009.67
   154.6 2010.06   159.4 2010.36   169.6 2011.33   177.5 2011.69   182.3 2012.04
#Mann= 3 ,-1,0
       0      .1       0    55.8    .045       0    73.7      .1       0
Bank Sta=55.8,73.7
XS Rating Curve= 0 ,0
Exp/Cntr(USF)=0,0
Exp/Cntr=0.3,0.1

Type RM Length L Ch R = 1 ,5453    ,109,109,109
XS GIS Cut Line= 4
2219749.61678299679773.195481516 2219750.8642915679792.323945345
2219752.52763618679844.3034666192219827.37814681679942.440802784
#Sta/Elev= 30
       0 2007.09       8 2006.12      12 2005.08      16 2003.41      24 1998.06
      28 1995.95    29.7 1995.44      32 1994.75      36 1994.47      44 1994.88
    46.11995.437      52 1997.06      56 1997.57      64 1997.78    72.3 1999.06
      83 1998.92    92.4 1999.41   105.8 1998.62   111.5 1998.91   114.4  1999.5
   120.1 2001.18   134.3 2006.02   137.7 2006.98   142.7  2007.9   152.8 2008.84
     160 2009.18   167.9 2010.15   172.9 2010.39   176.1  2010.8   194.6 2011.38
#Mann= 3 ,-1,0
       0      .1       0    29.7    .045       0    46.1      .1       0
Bank Sta=29.7,46.1
XS Rating Curve= 0 ,0
Exp/Cntr(USF)=0,0
Exp/Cntr=0.3,0.1

Type RM Length L Ch R = 1 ,5344    ,159.2,159.2,159.2
XS GIS Cut Line= 3
2219622.50521687679799.3881883922219669.97849547679876.479357605
2219793.15009185 679938.88192487
#Sta/Elev= 30
       0 2009.06     8.3 2007.22    16.2 2005.75    20.9 2005.11    25.6 2003.71
    30.3 2000.17      35 1996.14    39.7  1993.6    40.8 1993.32    44.4 1992.75
    58.5 1992.47    63.2 1992.63      651992.966    72.6 1994.43    77.3 1995.06
    98.6 1996.35   128.4 1996.98   146.8 1996.76   161.1 1997.17   164.1 1997.58
   170.1 1999.07   173.7 2000.22   180.6 2002.96   184.8 2004.37   190.9 2006.13
   196.9 2007.39   200.6 2007.96   205.8 2008.35   220.7 2009.01   228.6 2009.61
#Mann= 5 ,-1,0
       0      .1       0      10     .06       0    40.8    .045       0
      65     .06       0  150.54      .1       0
Bank Sta=40.8,65
XS Rating Curve= 0 ,0
Exp/Cntr(USF)=0,0
Exp/Cntr=0.3,0.1

Type RM Length L Ch R = 1 ,5185    ,146.8,146.8,146.8
XS GIS Cut Line= 4
  2219536.109949679964.3219468022219586.56993143679972.951340916
2219722.32988822 679985.500580622219787.35776669679994.627300405
#Sta/Elev= 30
       0 2013.69     4.1 2013.08    12.2 2010.85    28.5 2008.25    32.5 2007.08
    36.6 2006.25    40.6 2005.81    84.9 2006.69      89 2006.54      93 2005.91
      97  2004.6     101 2002.61   117.1 1991.03   121.1 1989.15   124.41988.399
   129.1 1987.89   137.2 1987.53   141.2 1987.75   143.41988.399   145.2 1988.93
   148.5 1990.74   153.2 1993.69   157.2 1995.55   169.3 1998.92   181.1 2003.24
   185.5  2004.3   213.6 2007.44   241.9 2008.78   249.1  2008.9   253.2 2009.29
#Mann= 3 ,-1,0
       0     .06       0   124.4    .045       0   143.4      .1       0
Bank Sta=124.4,143.4
XS Rating Curve= 0 ,0
Exp/Cntr(USF)=0,0
Exp/Cntr=0.3,0.1

Type RM Length L Ch R = 1 ,5038    ,173.1,173.1,173.1
XS GIS Cut Line= 3
2219486.42483897 680052.564443732219517.22751825680069.106623339
2219744.25467289680175.775160824
#Sta/Elev= 30
       0 2016.32    11.1 2016.15    15.6 2014.33    20.1 2011.72    24.7 2010.09
    37.2 2008.04    55.9 2006.27    97.4 2004.93   104.5 2004.47   109.4 2003.67
   113.4 2002.65   117.8 2000.29     131 1988.58   135.4 1985.35   138.6 1984.08
   144.3 1982.97     148 1982.89   153.1 1983.76   166.4 1989.48   170.8 1992.44
   175.5 1996.37   179.6 1998.75   184.6 2001.13   190.6 2002.76     215 2005.19
   223.8 2005.49   232.7 2005.28   250.4  2006.5   259.2 2006.44   285.8 2008.65
#Mann= 5 ,-1,0
       0      .1       0   44.96     .06       0   138.6    .045       0
   153.1     .06       0  154.96      .1       0
Bank Sta=138.6,153.1
XS Rating Curve= 0 ,0
Exp/Cntr(USF)=0,0
Exp/Cntr=0.3,0.1

Type RM Length L Ch R = 1 ,4865    ,159.8,159.8,159.8
XS GIS Cut Line= 3
2219433.00617358680202.5920561892219625.68136904680325.549253289
2219652.01094166  680339.5656387
#Sta/Elev= 30
       0 2014.62     3.8 2014.46     7.1 2013.49      18 2007.99    22.7 2006.33
    46.5 2000.04    60.7 1996.74    70.2 1992.61    91.1 1985.24    98.7 1981.96
   100.51981.534   103.4 1981.08   117.6 1980.83   122.4 1980.91   123.8 1981.21
   131.2  1983.2   137.4 1984.16   141.4 1985.55   150.9 1990.33   160.3 1991.98
   169.8 1992.28   179.3 1993.73   193.6 1995.17   198.1 1995.34   203.1  1994.7
   207.8 1994.98   235.5 1995.04     242 1995.65   253.8 1995.34   258.4 1994.84
#Mann= 4 ,-1,0
       0     .06       0   100.5    .045       0   123.8     .06       0
     140      .1       0
Bank Sta=100.5,123.8
XS Rating Curve= 0 ,0
Exp/Cntr(USF)=0,0
Exp/Cntr=0.3,0.1

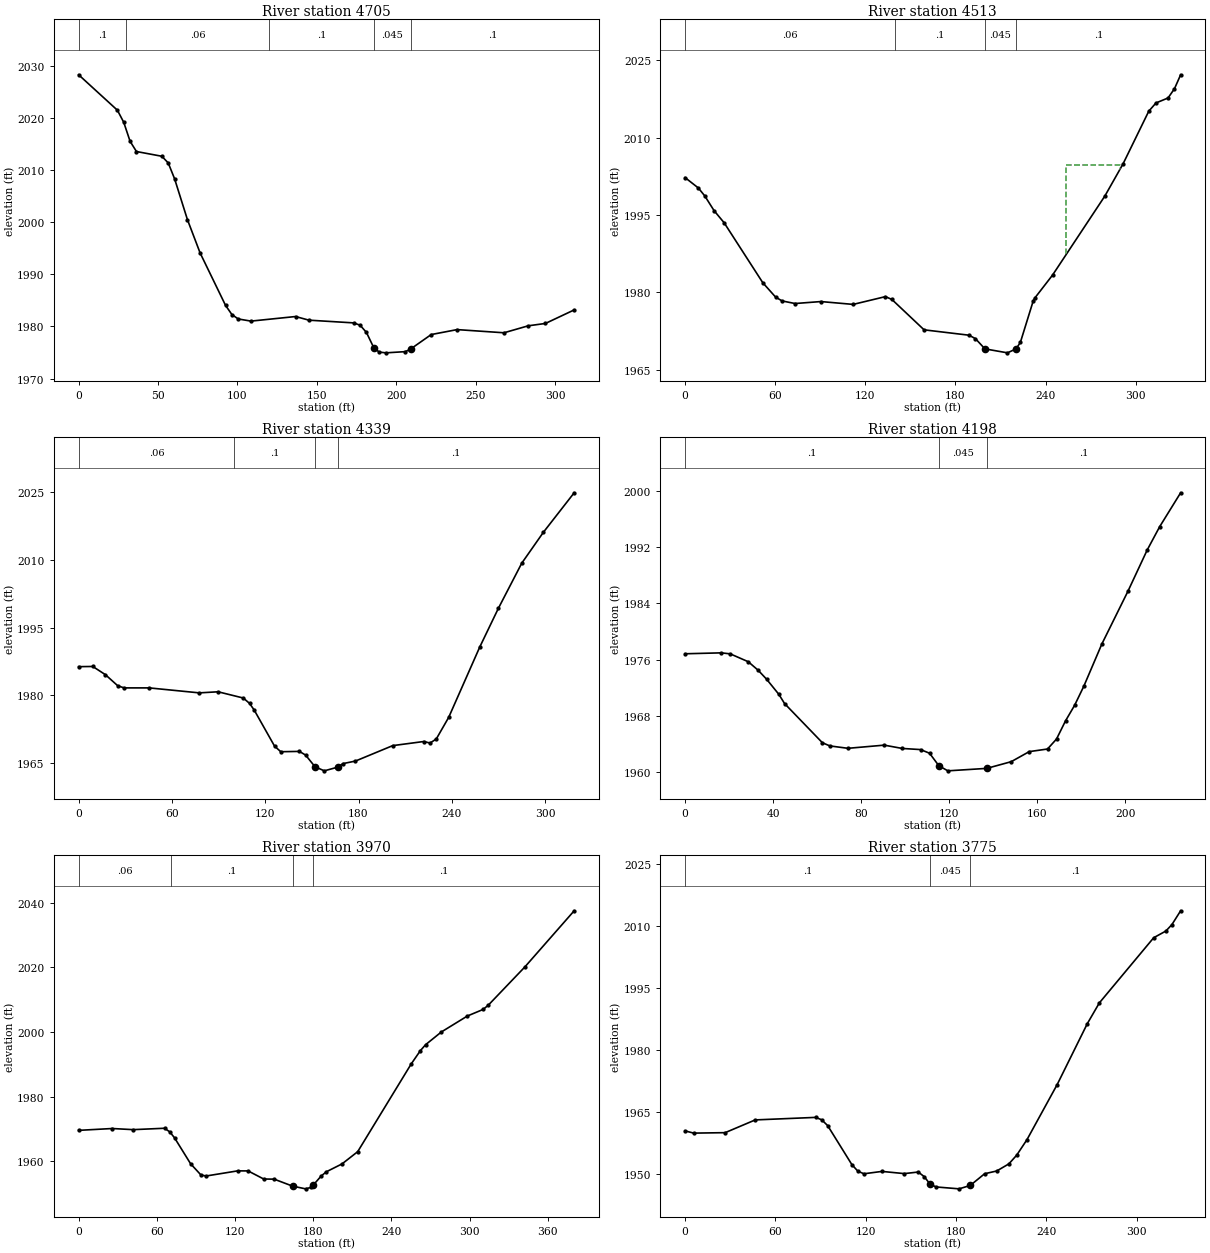
Type RM Length L Ch R = 1 ,4705    ,192.4,192.4,192.4
XS GIS Cut Line= 3
2219307.82868708680417.693043223 2219452.2268813680425.664634456
2219616.50783742680393.721115209
#Sta/Elev= 30
       0  2028.3    24.4  2021.5    28.4 2019.18    32.4 2015.53    36.4 2013.57
    52.4 2012.66    56.4 2011.38    60.4 2008.35    68.5  2000.5    76.5 1994.09
    92.5 1984.04    96.5 1982.28   100.5 1981.43   108.5 1981.02   136.6  1981.9
     145  1981.2   173.1 1980.68   177.2 1980.24   181.2 1978.85   185.9 1975.87
   189.3 1975.07   193.5 1974.93   205.7 1975.16     2091975.658     222 1978.44
   238.3 1979.39   267.8 1978.78   283.1 1980.12   293.9 1980.57     312 1983.17
#Mann= 5 ,-1,0
       0      .1       0      30     .06       0     120      .1       0
   185.9    .045       0     209      .1       0
Bank Sta=185.9,209
XS Rating Curve= 0 ,0
Exp/Cntr(USF)=0,0
Exp/Cntr=0.3,0.1

Type RM Length L Ch R = 1 ,4513    ,174.1,174.1,174.1
XS GIS Cut Line= 3
2219367.97969208680520.3865377862219500.43121295680572.237714564
2219676.00648481680638.463475002
#Sta/Elev= 30
       0 2002.24     8.8 2000.23    13.1 1998.69    19.3 1995.83      26 1993.48
    51.8 1981.83    60.3 1979.06    64.6 1978.33    73.2 1977.83    90.4 1978.21
   111.9 1977.66   133.4 1979.17   137.7 1978.61   159.1 1972.73     189 1971.69
   193.3 1971.02   199.6 1969.04   214.6 1968.27   220.31969.034   223.2 1970.29
   231.7 1978.28   232.8 1978.89   244.6 1983.33   279.4 1998.64   291.6 2004.92
   308.7 2015.12   313.5 2016.71   321.5 2017.67   325.8 2019.47   329.9 2022.17
#Mann= 4 ,-1,0
       0     .06       0     140      .1       0   199.6    .045       0
   220.3      .1       0
#XS Ineff= 1 ,-1
253.7209289.3263 2004.72
Permanent Ineff=
       T
Bank Sta=199.6,220.3
XS Rating Curve= 0 ,0
Exp/Cntr(USF)=0,0
Exp/Cntr=0.3,0.1

Type RM Length L Ch R = 1 ,4339    ,141.3,141.3,141.3
XS GIS Cut Line= 3
2219331.12289275680724.3224028042219455.47444982680739.723742441
2219648.84682526680740.294162428
#Sta/Elev= 30
       0 1986.36     9.1  1986.4    17.2 1984.59    25.2 1982.12    29.3 1981.66
    45.4 1981.66    77.6 1980.56    89.7  1980.8   105.9 1979.42   109.9 1978.24
   112.9 1976.77     126 1968.78     130 1967.54     142 1967.61     146 1966.79
     152 1964.22     158 1963.31   166.61964.123     170 1964.91     178 1965.47
     202 1968.89     222  1969.8     226 1969.46     230 1970.35     238 1975.14
     258 1990.72     270  1999.3     285 2009.26   298.9 2016.09   318.7 2024.83
#Mann= 4 ,-1,0
       0     .06       0     100      .1       0     152    .045       0
   166.6      .1       0
Bank Sta=152,166.6
XS Rating Curve= 0 ,0
Exp/Cntr(USF)=0,0
Exp/Cntr=0.3,0.1

Type RM Length L Ch R = 1 ,4198    ,227.9,227.9,227.9
XS GIS Cut Line= 2
2219348.28275927680845.5724454932219566.94375412680899.445444223
#Sta/Elev= 30
       0 1976.83    16.4 1976.96    20.5 1976.82    28.7  1975.7    33.2 1974.49
      37 1973.23    42.6 1971.07    45.2 1969.76    62.4 1964.19    65.8 1963.74
      74  1963.4    90.5 1963.85    98.7 1963.38     107 1963.22   111.1  1962.7
   115.31960.931   119.4  1960.2   137.1 1960.55   148.2  1961.5   156.4 1962.93
   164.7  1963.3   168.8 1964.72   172.9 1967.31     177  1969.5   181.2 1972.22
   189.4 1978.22   201.2 1985.68     210 1991.57   215.7  1994.9   225.2  1999.7
#Mann= 3 ,-1,0
       0      .1       0   115.3    .045       0   137.1      .1       0
Bank Sta=115.3,137.1
XS Rating Curve= 0 ,0
Exp/Cntr(USF)=0,0
Exp/Cntr=0.3,0.1

Type RM Length L Ch R = 1 ,3970    ,194.6,194.6,194.6
XS GIS Cut Line= 4
2219262.36069491681074.5115102972219313.55929148681075.477521553
2219546.36800417681089.9676903932219641.95110556681095.569699126
#Sta/Elev= 30
       0 1969.56    25.8 1970.13    41.8 1969.78    65.9 1970.21    69.9  1969.1
    73.6 1967.24    85.9 1959.23    93.9 1955.72    97.9 1955.44     122 1957.02
     130 1957.01     142  1954.5     150 1954.46   164.11952.307   174.1 1951.46
   178.1 1951.89   179.8 1952.53   186.1 1955.43   190.1 1956.75   202.1 1959.18
   214.1 1962.96   255.2 1990.14   262.2 1994.23   266.2 1996.07   278.3 2000.01
   298.3 2004.96   310.3 2006.98   314.3  2008.3   342.4 2020.15   380.2 2037.52
#Mann= 4 ,-1,0
       0     .06       0   71.21      .1       0   164.1    .045       0
   179.8      .1       0
Bank Sta=164.1,179.8
XS Rating Curve= 0 ,0
Exp/Cntr(USF)=0,0
Exp/Cntr=0.3,0.1

Type RM Length L Ch R = 1 ,3775    ,193.5,193.5,193.5
XS GIS Cut Line= 3
2219233.57411897681249.8346761672219301.19490689681252.732709935
2219562.01794601681272.052935055
#Sta/Elev= 30
       0 1960.41     5.7 1959.87    26.6 1959.98    46.6 1963.06    86.7 1963.67
    90.7  1963.1    94.7 1961.69   110.8 1952.26   114.8 1950.67   118.8 1950.05
   130.8 1950.62   145.6 1950.09   154.9 1950.47   158.9 1949.34   162.9 1947.47
   166.9 1946.86     182 1946.41   189.41947.223     199 1950.06     207 1950.72
   215.1 1952.44   220.3 1954.55   227.1 1958.28   247.2 1971.61   267.2 1986.31
   275.2 1991.33   311.3 2007.07   319.4 2008.69   323.4 2010.24   329.2 2013.58
#Mann= 3 ,-1,0
       0      .1       0   162.9    .045       0   189.4      .1       0
Bank Sta=162.9,189.4
XS Rating Curve= 0 ,0
Exp/Cntr(USF)=0,0
Exp/Cntr=0.3,0.1

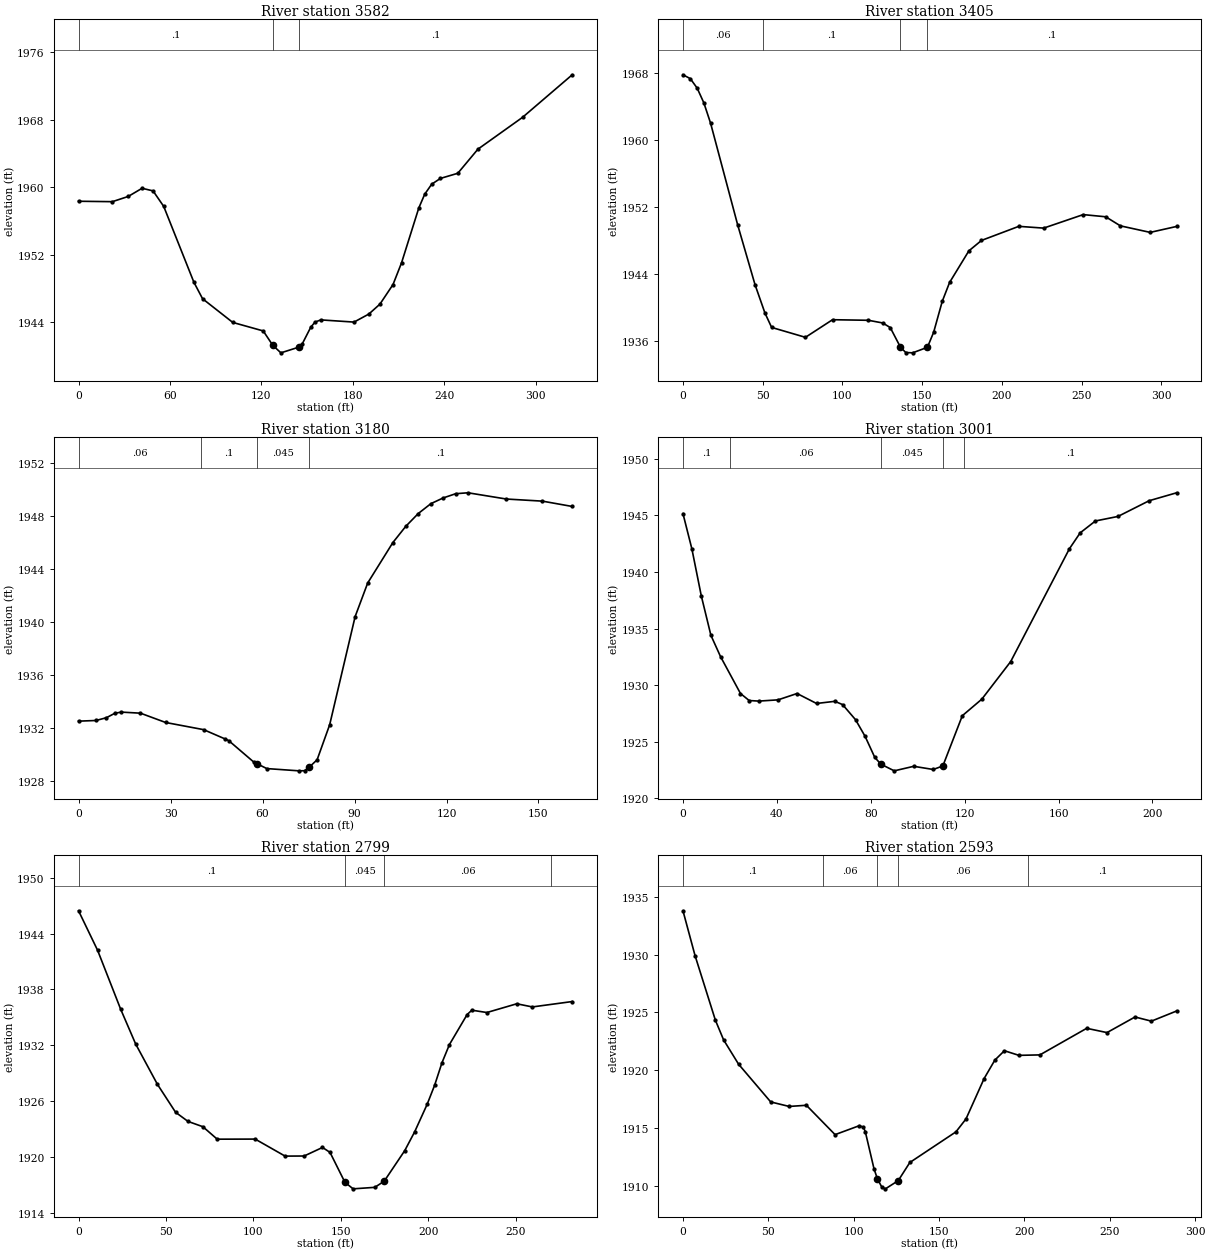
Type RM Length L Ch R = 1 ,3582    ,176.6,176.6,176.6
XS GIS Cut Line= 3
2219253.07323507681333.3409825182219285.27361027681367.926570696
 2219464.1645836681579.017919227
#Sta/Elev= 30
       0 1958.32    22.2 1958.27    32.6 1958.89    41.7 1959.86    48.9 1959.55
    55.9 1957.71    75.7 1948.71    81.4 1946.75   101.2 1943.94   121.2 1942.93
   127.5 1941.22   132.8 1940.33   144.5    1941   146.7 1941.35   152.4 1943.37
   155.2 1943.98     159 1944.24   180.8 1943.98   190.5 1944.93   197.8 1946.11
   206.4 1948.44     212 1951.02   223.3 1957.52   227.2 1959.16   231.8 1960.35
   237.5 1961.03   248.9 1961.64   262.1  1964.5   291.4 1968.28     324 1973.33
#Mann= 3 ,-1,0
       0      .1       0   127.5    .045       0   144.5      .1       0
Bank Sta=127.5,144.5
XS Rating Curve= 0 ,0
Exp/Cntr(USF)=0,0
Exp/Cntr=0.3,0.1

Type RM Length L Ch R = 1 ,3405    ,225.3,225.3,225.3
XS GIS Cut Line= 3
2219150.77010432681412.839921193 2219185.9812146681511.431029979
2219290.83207633681687.486581383
#Sta/Elev= 30
       0 1967.74     4.6 1967.28     8.9 1966.15    13.1 1964.39    17.3 1961.98
    34.3 1949.85    45.2 1942.71    51.4 1939.34    55.6 1937.62    76.8 1936.44
    93.8 1938.54   116.3 1938.47   125.3 1938.15     130  1937.6   136.41935.262
   139.7 1934.63     144 1934.59   153.3 1935.25   157.2 1937.04   162.6 1940.73
   167.2 1942.98   179.3 1946.75   187.2 1947.99   210.6 1949.67   226.2 1949.46
     251 1951.07   265.1 1950.81   274.3 1949.73     293 1948.95   309.6 1949.66
#Mann= 4 ,-1,0
       0     .06       0      50      .1       0   136.4    .045       0
   153.3      .1       0
Bank Sta=136.4,153.3
XS Rating Curve= 0 ,0
Exp/Cntr(USF)=0,0
Exp/Cntr=0.3,0.1

Type RM Length L Ch R = 1 ,3180    ,178.6,178.6,178.6
XS GIS Cut Line= 3
 2219100.5669263681716.5126459812219212.11572367681689.259246623
2219257.74932259681682.287446788
#Sta/Elev= 30
       0 1932.54     5.7 1932.59     9.1  1932.8    11.9 1933.14      14 1933.22
    20.2 1933.14    28.4 1932.44    40.8  1931.9    47.8  1931.2      49 1931.07
    57.2 1929.45    58.11929.347    61.4 1928.97    71.9  1928.8    73.7 1928.81
    75.2 1929.07    77.8 1929.63    81.9 1932.27    90.2 1940.41    94.3 1942.94
   102.5 1945.98   106.7  1947.2   110.8 1948.17   114.9 1948.91   118.9 1949.34
     123 1949.66     127 1949.73   139.5 1949.26   151.3  1949.1     161  1948.7
#Mann= 4 ,-1,0
       0     .06       0      40      .1       0    58.1    .045       0
    75.2      .1       0
Bank Sta=58.1,75.2
XS Rating Curve= 0 ,0
Exp/Cntr(USF)=0,0
Exp/Cntr=0.3,0.1

Type RM Length L Ch R = 1 ,3001    ,201.7,201.7,201.7
XS GIS Cut Line= 3
2219016.48618565681843.988732646 2219065.2570945681853.742914416
2219220.29724684681895.326531435
#Sta/Elev= 30
       0 1945.16     3.8 1942.04     7.8  1937.9    11.9 1934.41      16 1932.53
    24.5 1929.27    28.2 1928.65    32.3  1928.6    40.5 1928.71    48.6 1929.27
    56.9 1928.39    64.7 1928.58      68 1928.29    73.5 1926.96    77.6 1925.48
    81.7 1923.63    84.3 1923.03      90 1922.44    98.3 1922.84   106.6 1922.56
   110.7 1922.87     119 1927.31   127.3 1928.77   139.6 1932.09   164.6 1942.05
   169.2 1943.46   175.7 1944.51   185.3 1944.91   198.6  1946.3   210.3    1947
#Mann= 5 ,-1,0
       0      .1       0      20     .06       0    84.3    .045       0
   110.7     .06       0  119.74      .1       0
Bank Sta=84.3,110.7
XS Rating Curve= 0 ,0
Exp/Cntr(USF)=0,0
Exp/Cntr=0.3,0.1

Type RM Length L Ch R = 1 ,2799    ,206,206,206
XS GIS Cut Line= 2
2218881.56871947681993.702975562 2219145.8693991682092.815730426
#Sta/Elev= 30
       0 1946.46    10.9 1942.21    24.1 1935.87    32.7 1932.12    45.1  1927.8
    55.5 1924.79    62.6 1923.81    71.1 1923.24    79.3  1921.9     101 1921.91
   118.1 1920.08     129 1920.09   139.5 1921.01   143.8 1920.48   152.3 1917.27
     157 1916.56   169.4 1916.72   174.81917.385   186.5 1920.66   192.2 1922.69
   199.3 1925.63   203.6 1927.69   207.8 1930.11   212.1 1932.08   222.2  1935.3
   224.9 1935.77   233.5 1935.52   250.6 1936.46   259.5 1936.12   282.3  1936.7
#Mann= 4 ,-1,0
       0      .1       0   152.3    .045       0   174.8     .06       0
     270      .1       0
Bank Sta=152.3,174.8
XS Rating Curve= 0 ,0
Exp/Cntr(USF)=0,0
Exp/Cntr=0.3,0.1

Type RM Length L Ch R = 1 ,2593    ,192.8,192.8,192.8
XS GIS Cut Line= 3
2218804.19121786682091.0769101652218845.92290412682137.155647076
 2218999.8084972682304.082392111
#Sta/Elev= 30
       0 1933.79     7.1  1929.9      19 1924.32    23.8 1922.62    32.6 1920.51
    51.4 1917.25    62.2 1916.86    72.3 1916.96    89.1 1914.42   103.4  1915.2
   105.7 1915.05   106.8 1914.68   111.9 1911.47   113.91910.594   116.6 1909.85
   118.6 1909.73   126.1 1910.44   132.9 1912.01   159.9 1914.66   165.8 1915.78
   176.4 1919.27   182.7 1920.87   188.3 1921.68   196.8 1921.28   209.1 1921.32
   236.5 1923.62   248.4 1923.25   264.8  1924.6   274.4 1924.24   289.2 1925.12
#Mann= 5 ,-1,0
       0      .1       0   82.17     .06       0   113.9    .045       0
   126.1     .06       0  202.17      .1       0
Bank Sta=113.9,126.1
XS Rating Curve= 0 ,0
Exp/Cntr(USF)=0,0
Exp/Cntr=0.3,0.1