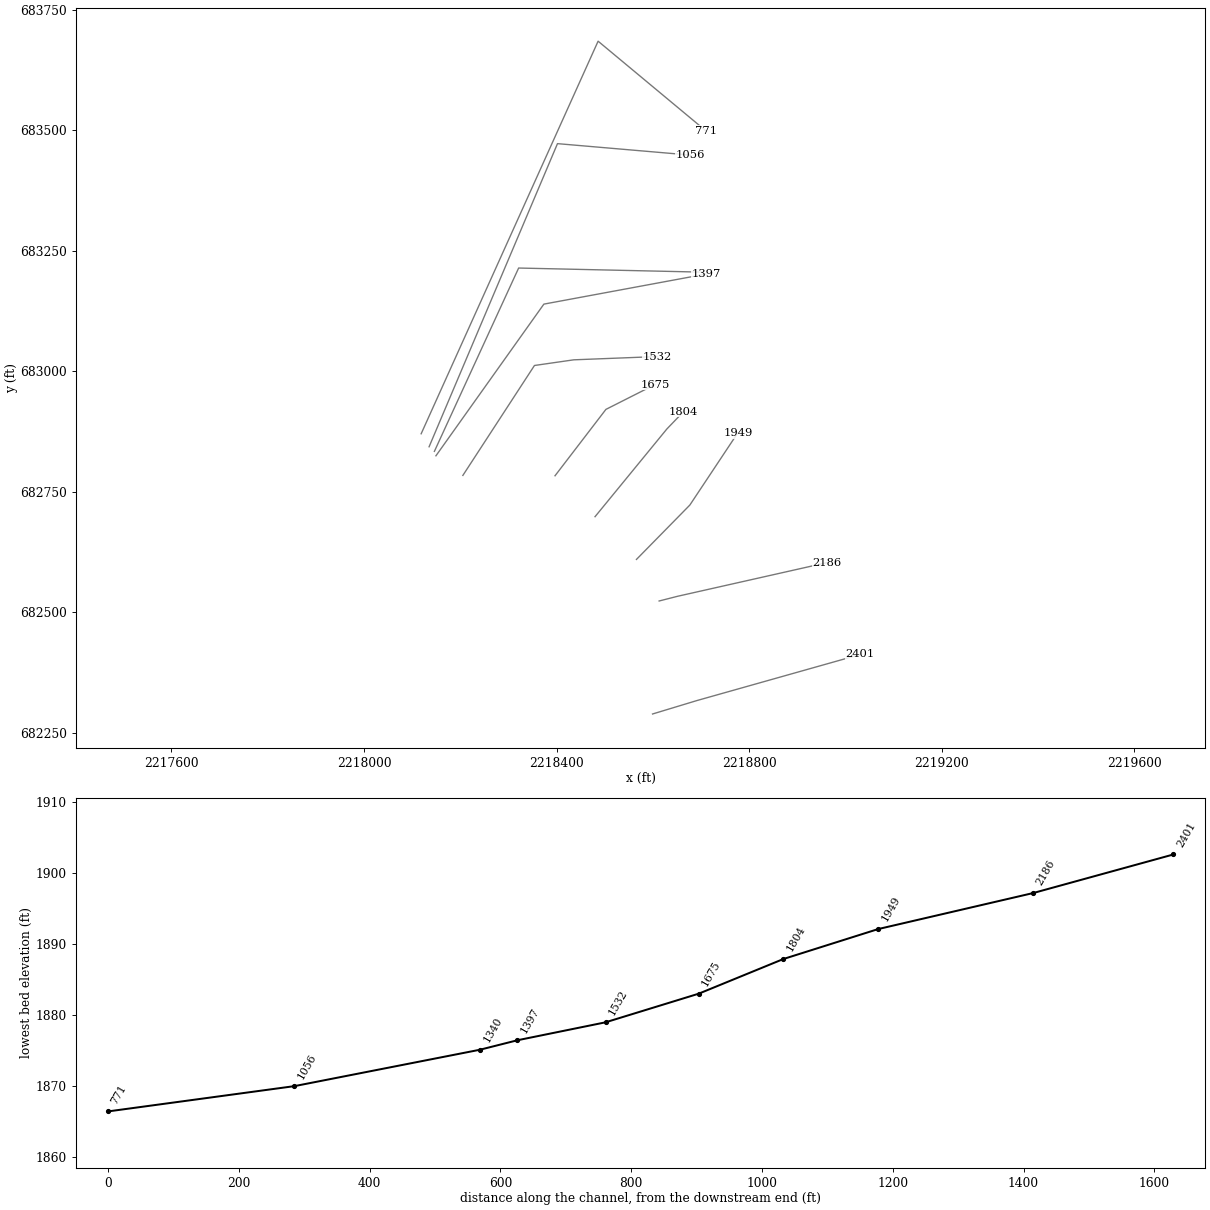
HEC-RAS study LAURELRN2.prj: LAURELRN2

--- LAURELRN2.g01 (geometry) --- (continued)

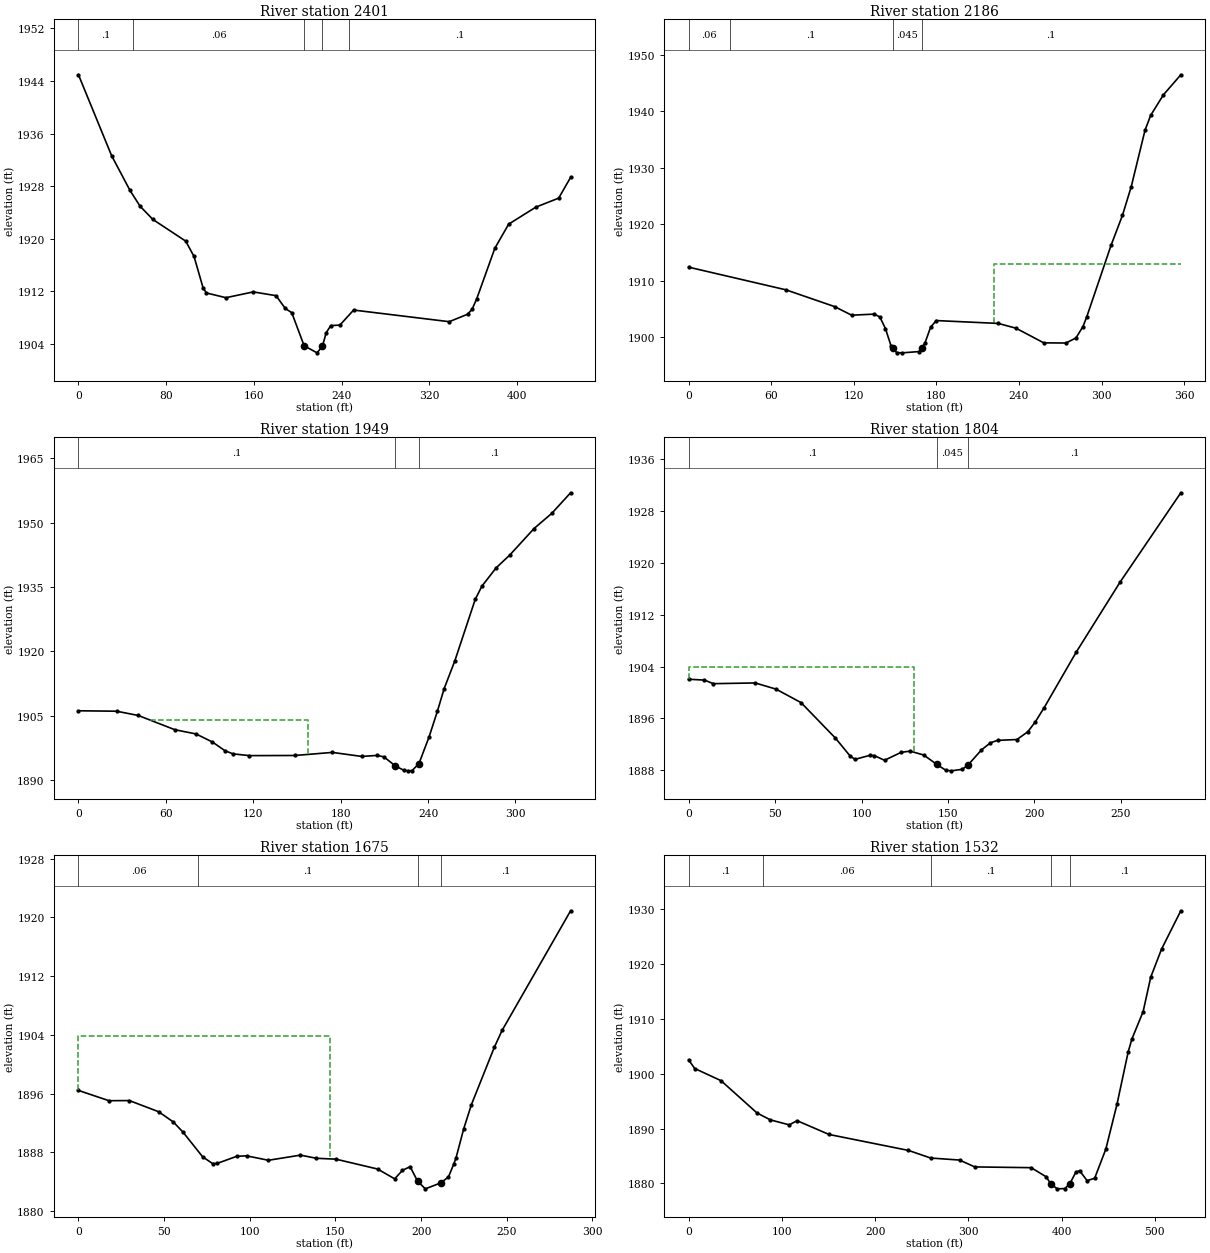
Type RM Length L Ch R = 1 ,2401    ,214.3,214.3,214.3
XS GIS Cut Line= 3
2218599.21931545 682288.902596312218691.52705769 682316.80958815
2219030.70434313682412.337367909
#Sta/Elev= 30
       0 1944.95    30.2 1932.65      47 1927.35    56.2 1924.95    67.9 1922.93
    97.8 1919.64   105.4  1917.3   113.7  1912.5   116.7 1911.75   134.5 1911.03
   159.4 1911.91   180.2 1911.34   188.5 1909.41   194.5 1908.75   205.81903.716
   217.6 1902.64   222.51903.663   225.9  1905.7   230.1 1906.79   238.4 1906.86
   250.9 1909.15   338.1 1907.38   354.8 1908.51   358.9 1909.25   363.1 1910.82
   379.7 1918.55   392.3 1922.22   417.1 1924.81   437.9 1926.18   448.8 1929.34
#Mann= 5 ,-1,0
       0      .1       0      50     .06       0   205.8    .045       0
   222.5     .06       0  246.43      .1       0
Bank Sta=205.8,222.5
XS Rating Curve= 0 ,0
Exp/Cntr(USF)=0,0
Exp/Cntr=0.3,0.1

Type RM Length L Ch R = 1 ,2186    ,237.3,237.3,237.3
XS GIS Cut Line= 3
2218612.91254356682523.2931133452218651.64476487682533.152224223
2218961.50253534682602.870222579
#Sta/Elev= 30
       0 1912.39    70.6 1908.38   106.1  1905.4   118.4 1903.88   134.8 1904.07
   138.9 1903.57     143  1901.5   147.1 1898.41   148.21898.071   151.2 1897.24
   155.3 1897.21   167.6 1897.44   169.31898.055   171.7 1898.96   175.8 1901.75
   179.9 1902.93     225 1902.42   237.9 1901.57     258 1898.98   274.2 1898.95
   281.4 1899.85   286.5 1901.86   289.3 1903.62     307 1916.32   315.2 1921.57
   321.6 1926.67   331.6 1936.66   335.7 1939.29     345 1942.94   357.6 1946.48
#Mann= 4 ,-1,0
       0     .06       0      30      .1       0   148.2    .045       0
   169.3      .1       0
#XS Ineff= 2 , 0
                          221.52         1912.91
Permanent Ineff=
       F       F
Bank Sta=148.2,169.3
XS Rating Curve= 0 ,0
Exp/Cntr(USF)=0,0
Exp/Cntr=0.3,0.1

Type RM Length L Ch R = 1 ,1949    ,144.7,144.7,144.7
XS GIS Cut Line= 3
 2218565.7826576682609.4942380892218676.69765498682722.310635429
2218776.20425264682871.887431902
#Sta/Elev= 30
       0 1906.14    26.2 1906.04    41.1 1905.04    66.2 1901.72    80.7 1900.74
      92 1898.85   100.5 1896.84   106.1 1896.09   117.4 1895.68   148.6 1895.71
   174.3 1896.43   194.5 1895.49   204.9 1895.72   209.7  1895.4   217.6 1893.26
   223.4 1892.26   226.3 1892.13   229.1  1892.2   233.81893.838   240.7 1900.02
   246.4 1905.99   251.1 1911.33   258.4 1917.78   272.4 1932.11     277 1935.21
   286.8 1939.49   296.2 1942.49   312.8 1948.65     325  1952.2   337.9 1956.99
#Mann= 3 ,-1,0
       0      .1       0   217.6    .045       0   233.8      .1       0
#XS Ineff= 1 ,-1
48.92202157.9303 1903.89
Permanent Ineff=
       T
Bank Sta=217.6,233.8
XS Rating Curve= 0 ,0
Exp/Cntr(USF)=0,0
Exp/Cntr=0.3,0.1

Type RM Length L Ch R = 1 ,1804    ,129.7,129.7,129.7
XS GIS Cut Line= 4
2218479.76803908 682698.156517292218504.79140145682728.664988176
2218629.01619852682880.1431846042218663.24139771682915.635983767
#Sta/Elev= 30
       0 1902.05     9.1 1901.92    14.3 1901.37    38.5 1901.48    50.5 1900.53
      65 1898.45    84.9 1892.97    93.4 1890.21    96.2 1889.69   104.8 1890.31
   107.4 1890.27   113.3 1889.55   122.9 1890.77   128.1 1890.96     136 1890.36
   143.6  1888.9   148.8    1888     152 1887.92   158.3 1888.16   161.6 1888.82
   169.4 1891.15   174.6 1892.25   178.7 1892.62   189.9 1892.75   196.2 1893.95
   200.5 1895.46   205.7 1897.69   224.1 1906.19   249.6 1917.05   284.7 1930.82
#Mann= 3 ,-1,0
       0      .1       0   143.6    .045       0   161.6      .1       0
#XS Ineff= 2 , 0
        130.6446 1903.89
Permanent Ineff=
       T       F
Bank Sta=143.6,161.6
XS Rating Curve= 0 ,0
Exp/Cntr(USF)=0,0
Exp/Cntr=0.3,0.1

Type RM Length L Ch R = 1 ,1675    ,142.4,142.4,142.4
XS GIS Cut Line= 3
2218396.64007402682783.0334564642218502.34459989682920.722035415
2218603.90223264682971.976274231
#Sta/Elev= 30
       0 1896.43    17.8 1895.03    29.7 1895.05    46.8 1893.53    55.4 1892.13
    61.1 1890.73    72.5 1887.39    78.3 1886.47    81.1  1886.5    92.5 1887.47
    98.2 1887.52   110.9 1886.92   129.6 1887.62   138.9 1887.19   150.3 1887.07
   174.6 1885.73   184.6 1884.39   189.1 1885.54   193.6 1886.05     198 1884.06
   202.5 1883.03   211.5 1883.84     216 1884.65     219 1886.35   220.4 1887.24
   224.9 1891.21   229.4  1894.5   242.8 1902.32   247.3  1904.6   287.3 1920.89
#Mann= 4 ,-1,0
       0     .06       0      70      .1       0     198    .045       0
   211.5      .1       0
#XS Ineff= 2 , 0
        146.8878 1903.89
Permanent Ineff=
       T       F
Bank Sta=198,211.5
XS Rating Curve= 0 ,0
Exp/Cntr(USF)=0,0
Exp/Cntr=0.3,0.1

Type RM Length L Ch R = 1 ,1532    ,134.9,134.9,134.9
XS GIS Cut Line= 4
2218205.24353802682783.7713939472218353.93421726683011.786155111
2218435.59548134683023.5316773542218608.51149617683030.293756146
#Sta/Elev= 30
       0 1902.51     6.5 1900.95    34.7 1898.73    73.3 1892.84    87.6 1891.58
   107.9 1890.67   116.3 1891.43   150.5 1888.92   235.7 1886.01   259.5 1884.62
   290.6 1884.25   306.8    1883   367.3 1882.86   383.3 1881.21   388.71879.844
   395.3    1879   403.3 1879.05   408.61879.879   415.3 1882.06   419.3 1882.31
   427.3 1880.49   435.4 1880.93   447.4 1886.25   459.4 1894.46   471.4 1904.01
   475.4 1906.35   487.4 1911.33   495.5 1917.59   507.1 1922.71   527.8 1929.72
#Mann= 5 ,-1,0
       0      .1       0      80     .06       0     260      .1       0
   388.7    .045       0   408.6      .1       0
Bank Sta=388.7,408.6
XS Rating Curve= 0 ,0
Exp/Cntr(USF)=0,0
Exp/Cntr=0.3,0.1

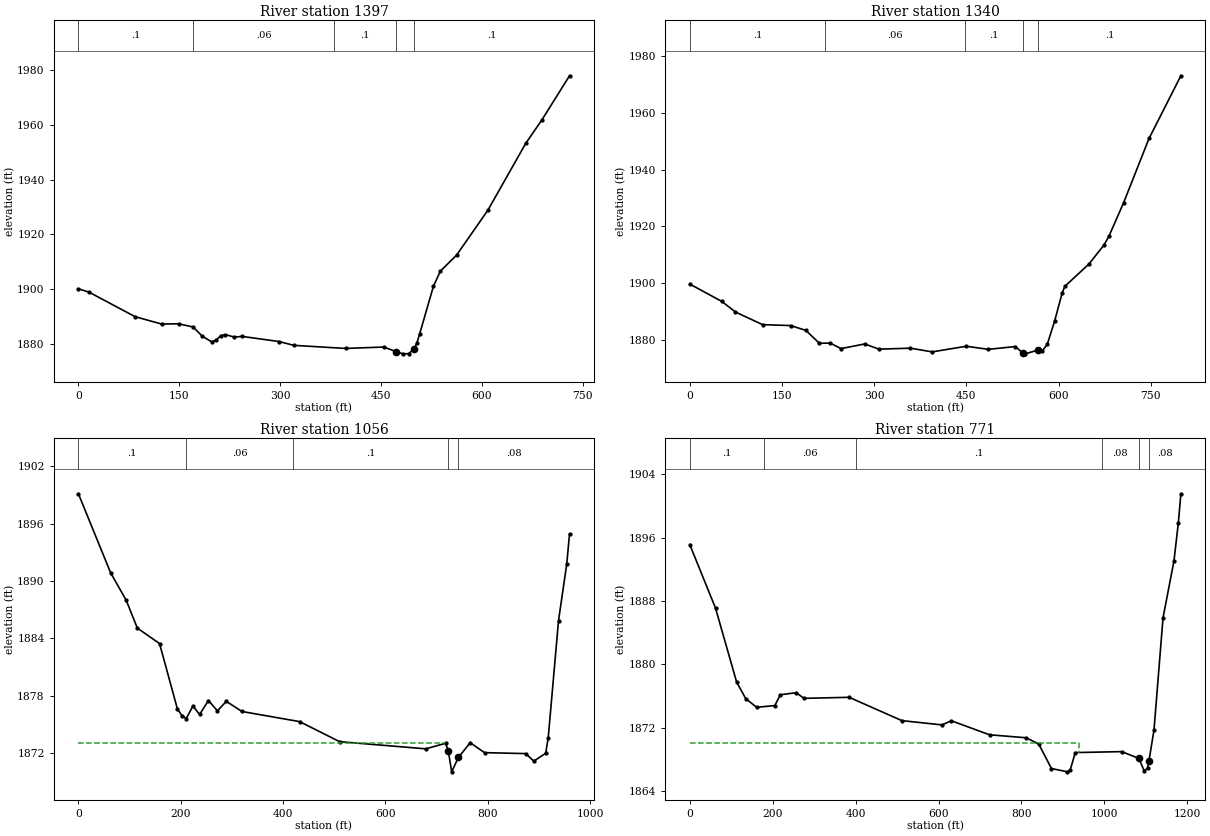
Type RM Length L Ch R = 1 ,1397    ,57.1,57.1,57.1
XS GIS Cut Line= 3
2218149.29218594682824.4358762892218373.50059528683139.069575843
2218711.52249644683201.666733938
#Sta/Elev= 30
       0 1900.18    15.6 1898.97    84.4    1890   123.7 1887.33   148.9 1887.42
   170.4 1886.26   184.2  1882.9     198 1880.84   204.9 1881.49   211.7 1883.11
   218.6 1883.48   231.8 1882.58   243.5 1882.82     298 1880.96   320.2 1879.57
   397.2 1878.44   454.2 1878.95   471.9 1877.31   482.6 1876.47   490.8 1876.54
   498.9 1878.15     503 1880.31   507.2 1883.61   527.7 1901.02     538 1906.59
   562.1 1912.41   608.7  1928.8     665 1953.16   689.1 1961.74   730.1 1977.81
#Mann= 5 ,-1,0
       0      .1       0     170     .06       0     380      .1       0
   471.9    .045       0   498.9      .1       0
Bank Sta=471.9,498.9
XS Rating Curve= 0 ,0
Exp/Cntr(USF)=0,0
Exp/Cntr=0.3,0.1

Type RM Length L Ch R = 1 ,1340    ,283.9,283.9,283.9
XS GIS Cut Line= 3
2218146.09756807682833.633233077 2218321.0776511683213.916544507
2218701.38266731683205.436207796
#Sta/Elev= 30
       0  1899.7    52.3 1893.57    74.4 1889.85   118.4 1885.42   164.1 1885.09
   188.8  1883.4   210.9 1878.86   228.5 1878.92   246.1 1876.98   284.7 1878.62
   307.7 1876.79     359 1877.13   394.5 1875.83   449.7 1877.81   485.7 1876.72
   529.7 1877.71   541.61875.465   545.7 1875.14     5671876.486   573.7 1876.18
   581.7 1878.52   593.7 1886.74   605.8 1896.48   610.2 1898.88   649.4 1906.74
   673.8 1913.39   681.8 1916.45   705.8 1928.29   747.2 1950.93     799    1973
#Mann= 5 ,-1,0
       0      .1       0     220     .06       0  448.61      .1       0
   541.6    .045       0     567      .1       0
Bank Sta=541.6,567
XS Rating Curve= 0 ,0
Exp/Cntr=0.3,0.1

Type RM Length L Ch R = 1 ,1056    ,284.9,284.9,284.9
XS GIS Cut Line= 3
2218135.09577045682843.1840501382218401.76563067683471.931873772
2218677.54143748683448.241722002
#Sta/Elev= 30
       0 1899.13      63 1890.85    93.4 1887.98   115.1 1885.07   158.6 1883.44
   193.3 1876.63     202 1875.91   210.7 1875.59   223.8  1876.9   236.8 1876.02
   254.2 1877.48   271.6  1876.4   289.1 1877.39   319.6 1876.33   432.3 1875.27
   510.5 1873.17   678.9 1872.42   717.5    1873   722.81872.237   729.5 1870.01
   742.61871.515   765.7 1873.06   793.8 1872.02   874.1 1871.92   890.1 1871.13
   913.3 1871.96   918.2 1873.58   938.3 1885.83   954.4 1891.78   959.8 1894.91
#Mann= 5 ,-1,0
       0      .1       0     210     .06       0     420      .1       0
   722.8    .045       0   742.6     .08       0
#XS Ineff= 2 , 0
          716.62 1872.99
Permanent Ineff=
       F       F
Bank Sta=722.8,742.6
XS Rating Curve= 0 ,0
Exp/Cntr=0.3,0.1

Type RM Length L Ch R = 1 ,771     ,,,
XS GIS Cut Line= 3
2218118.61933421682870.1471708312218486.12817279683684.439641882
 2218709.9956527683498.502515164
#Sta/Elev= 30
       0 1895.12    62.1  1887.1     113 1877.78     135 1875.68   161.3 1874.59
   205.2 1874.81   218.4 1876.17   256.6 1876.43   275.4 1875.72   384.5 1875.85
   511.5 1872.91   608.2 1872.37   630.9 1872.89   723.1 1871.12   810.8 1870.75
   841.5 1869.97   872.3 1866.87     911 1866.45   917.3 1866.64   929.8 1868.88
  1041.6    1869  1083.2 1868.14    1096 1866.56    1104 1866.91  1107.4 1867.81
  1119.6 1871.72  1141.4 1885.88  1167.7 1893.03  1178.4 1897.87  1184.4 1901.52
#Mann= 6 ,-1,0
       0      .1       0     180     .06       0     400      .1       0
  993.38     .08       0  1083.2    .045       0  1107.4     .08       0
#XS Ineff= 2 , 0
          938.31 1870.07
Permanent Ineff=
       F       F
Bank Sta=1083.2,1107.4
XS Rating Curve= 0 ,0
Exp/Cntr(USF)=0,0
Exp/Cntr=0.3,0.1
LCMann Table=0

Chan Stop Cuts=-1
Use User Specified Reach Order=0
Composite Channel Slope=5